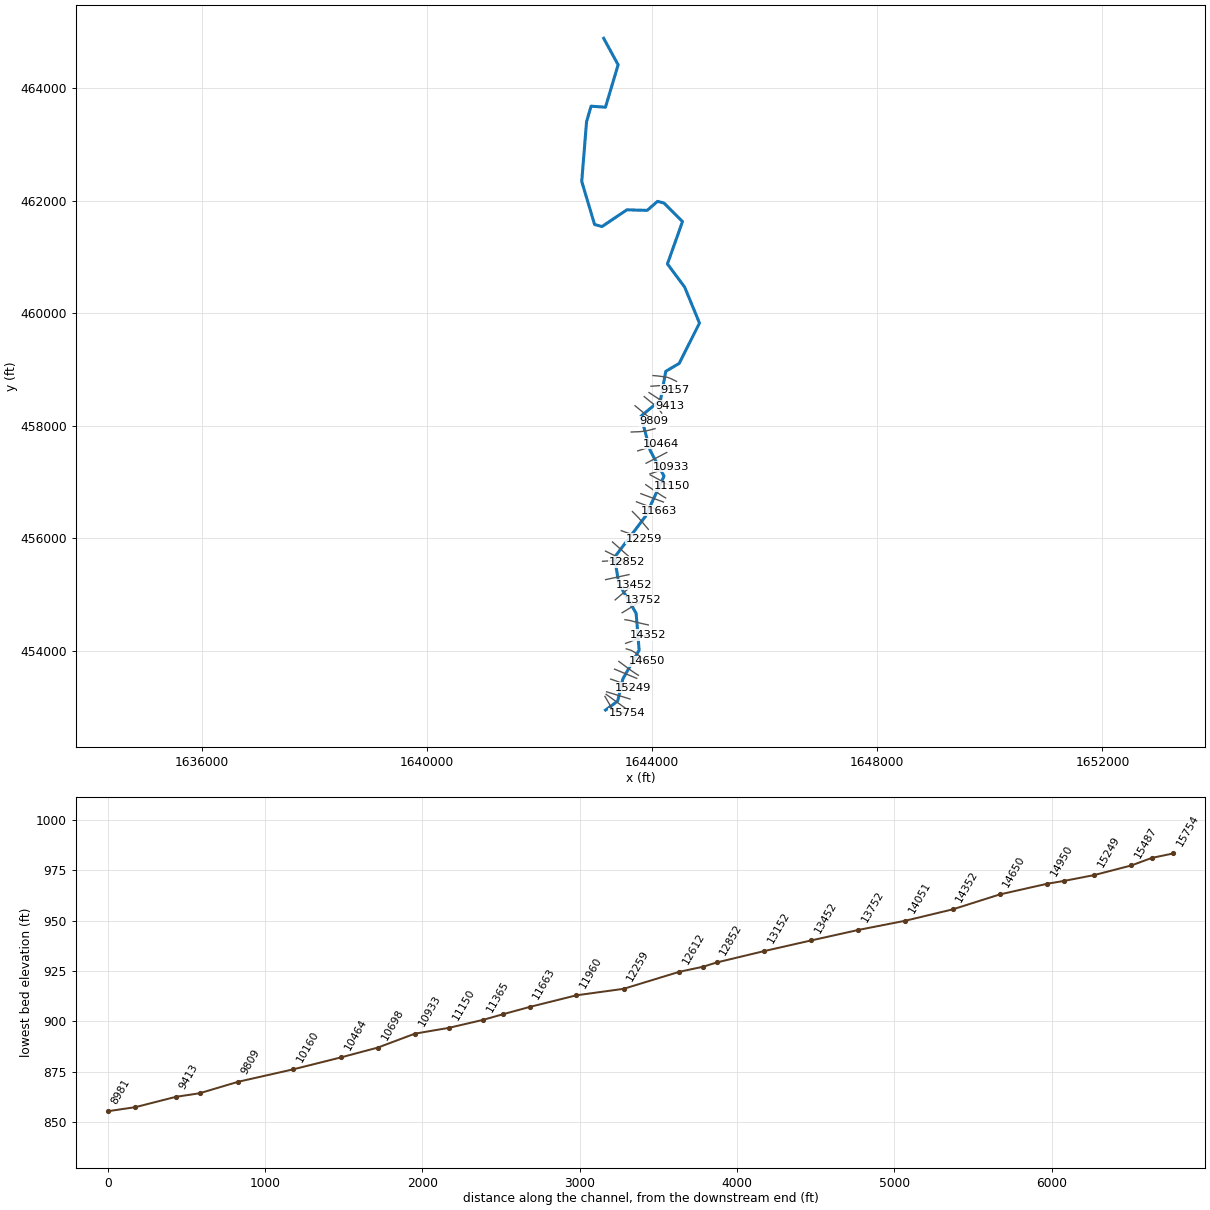
--- VallyRn.prj (project) ---

Proj Title=VallyRn
Current Plan=p01
Default Exp/Contr=0,0
English Units
Geom File=g01
Flow File=f01
Plan File=p01
BEGIN DESCRIPTION:
---------- MODELED AS PART OF WVEM CTP PROGRAM, 2025----------
Stream Name: Valley Run
Flood Zone: AFH
Marshall County, WV
HEC-RAS Version: RAS 6.6
Vertical Datum: NAVD88
Projection: NAD 1983 StatePlane West Virginia N FIPS 4701 (US Feet)
Terrain: 1-meter West Virginia FEMA R3 South Central (collected 2018-2019)
Land Use: 2024 NLCD
Hydrologic Method:
Duda et al., "Estimation of magnitude and frequency of floods for rural, unregulated streams in and near Virginia and West Virginia." September 8, 2025.
Additional Model Notes:
None
END DESCRIPTION:
DSS File=dss
DSS Export Rating Curves= 0
DSS Export Rating Curve Sorted= 0
DSS Export Volume Flow Curves= 0
DXF OffsetX= 0
DXF OffsetY= 0
DXF ScaleX= 0
DXF ScaleY= 0

--- VallyRn.p01 (plan) ---

Plan Title=Floodplain
Program Version=6.60
Short Identifier=Floodplain
Geom File=g01
Flow File=f01
Subcritical Flow
K Sum by GR= 0
Std Step Tol= 0.01
Critical Tol= 0.01
Num of Std Step Trials= 20
Max Error Tol= 0.3
Flow Tol Ratio= 0.001
Split Flow NTrial= 30
Split Flow Tol= 0.02
Split Flow Ratio= 0.02
Log Output Level= 0
Friction Slope Method= 1
Unsteady Friction Slope Method= 2
Unsteady Bridges Friction Slope Method= 1
Parabolic Critical Depth
Global Vel Dist= 0 , 0 , 0
Global Log Level= 0
CheckData=False
Encroach Param=-1 ,0,0, 0
Flow Ratio Tolerance=0.1
Flow Ratio Min Ratio=0.5
Flow Ratio Max Ratio=4
Flow Ratio Max Iterations= 10
Computation Interval=0.1SEC
Output Interval=1SEC
Instantaneous Interval=Max Profile
Mapping Interval=1HOUR
Computation Time Step Use Courant=        0
Computation Time Step Use Time Series=    0
Computation Time Step Count To Double=0
Computation Time Step Max Doubling=0
Computation Time Step Max Halving=0
Computation Time Step Residence Courant=0
Run HTab= 0
Run UNet= 0
Run Sediment= 0
Run PostProcess= 0
Run WQNet= 0
Run RASMapper=-1
UNET Theta= 0
UNET Theta Warmup= 0
UNET ZTol= 0
UNET ZSATol= 0
UNET MxIter= 0
UNET Max Iter WO Improvement= 0
UNET MaxInSteps= 0
UNET DtIC= 0
UNET DtMin= 0
UNET MaxCRTS= 0
UNET WFStab= 0
UNET SFStab= 0
UNET WFX= 1
UNET SFX= 1
UNET Gravity=32.17405
UNET 1D Methodology=Finite Difference
UNET DSS MLevel= 1
UNET Pardiso=0
UNET DZMax Abort= 0
UNET Use Existing IB Tables= 0
UNET Froude Reduction=False
UNET Froude Limit= 0
UNET Froude Power= 0
UNET D1 Cores= 0
UNET WindReference=Eulerian
UNET WindDragFormulation=Hsu (1988)
UNET D2 Coriolis=0
UNET D2 Cores= 0
UNET D2 Theta= 1
UNET D2 Theta Warmup= 1
UNET D2 Z Tol= 0.01
UNET D2 Volume Tol= 0.01
UNET D2 Max Iterations= 20
UNET D2 Advanced Convergence=0
UNET D2 WS Max Tol=0.15
UNET D2 WS RMS Tol=0.002
UNET D2 WS Stall Tol=1
UNET D2 Equation= 0
UNET D2 RampUpFraction=0.1
UNET D2 TimeSlices= 1
UNET D2 Turbulence Formulation=Non-Conservative (original)
UNET D2 Eddy Viscosity=0.3
UNET D2 Transverse Eddy Viscosity=0.1
UNET D2 Smagorinsky Mixing=0
UNET D2 BCVolumeCheck=0
UNET D2 Cores=0
UNET D2 SolverType=PARDISO (Direct)
UNET D2 Minimum Iterations= 3
UNET D2 Maximum Iterations= 30
UNET D2 Restart Number= 10
UNET D2 Relaxation Coeff=1.3
UNET D2 SOR Precondition Iterations= 10
UNET D2 ILUT Maximum Fill= 8
UNET D2 ILUT Tolerance=1E-08
UNET D2 Convergence Tolerance=0.00001
PS Theta= 1
PS WS Tol= 0.01
PS Volume Tol= 0.01
PS Max Iterations= 20
PS Equation= 0
PS Advance Time Step=-1
PS Target Courant=0.9
PS Time Slices= 1
PS Iterate With 2D=0
PS Project Initial WSE from DS=-1
PS Ramp Up Initial WSE from US=-1
PS Cores=0
UNET D1D2 MaxIter= 0
UNET D1D2 ZTol=0.01
UNET D1D2 QTol=0.1
UNET D1D2 MinQTol=1
DSS File=dss
Write IC File= 0
Write IC File at Fixed DateTime=0
Write IC File at Sim End=0
Echo Input=False
Echo Parameters=False
Echo Output=False
Write Detailed= 0
HDF Write Warmup=0
HDF Write Time Slices=0
HDF Flush=0
HDF Compression= 1
HDF Chunk Size= 1
HDF Spatial Parts= 1
HDF Use Max Rows=0
HDF Fixed Rows= 1
Calibration Method= 0
Calibration Iterations= 20
Calibration Max Change=0.05
Calibration Tolerance=0.2
Calibration Maximum=1.5
Calibration Minimum=0.5
Calibration Optimization Method= 1
WQ AD Non Conservative
WQ ULTIMATE=-1
WQ Max Comp Step=1HOUR
WQ Output Interval=15MIN
WQ Output Selected Increments= 0
WQ Create Restart=0
WQ Fixed Restart=0
WQ System Summary=0
WQ Write To DSS=0
Sorting and Armoring Iterations= 10
XS Update Threshold= 0.02
Bed Roughness Predictor= 0
Processes Affected by Predictor=Sediment Only
Hydraulics Update Threshold= 0.02
Energy Slope Method= 1
Volume Change Method= 1
Sediment Retention Method= 0
Sediment TS Multiplier= 1
Warm Up Method= 0
XS Weighting Method= 0
Number of US Weighted Cross Sections= 1
Number of DS Weighted Cross Sections= 1
Upstream XS Weight=0
Main XS Weight=1
Downstream XS Weight=0
Number of DS XS's Weighted with US Boundary= 1
Upstream Boundary Weight= 1
Weight of XSs Associated with US Boundary= 0
Number of US XS's Weighted with DS Boundary= 1
Downstream Boundary Weight= 0.5
Weight of XSs Associated with DS Boundary= 0.5
Percentile Method= 0
Sediment Output Level= 3
Mass or Volume Output= 0
Output Increment Type= 1
Profile and TS Output Increment= 1
Transport Output Increment 1
XS Output Flag= 0
XS Output Increment= 10
Read HDF5 Sediment Hotstart= 0
Sediment Hotstart Type= 0
Write Gradation File= 0
Read Gradation Hotstart= 0
Write HDF5 File= 1
Write Binary Output= 1
Write DSS Sediment File= 0
DSS Sediment Output Type= 1
SV Curve= 0
Specific Gage Flag= 0
Subcell Erosion Methods= 0
Subcell Deposition Methods= 0
Advection Scheme= 1
Matrix Solver= 0
Implicit Weighting Factor= 1
Maximum Outer Loop Convergence Iterations= 5
Convergence Maximum Absolute= 0.001
Convergence RMSE= 0.0001
Grain Fractions Max Abs Error= 0.001
Max Subgrid Regions= 1
Max Subgrid Length Scale= 3.402823E+38
Initial Layer Thickness= 3
Min Layer Thickness= 0.1
Max Layer Thickness= 6
Number of Layers= 5

--- VallyRn.f01 (steady flow) ---

Flow Title=Flow
Program Version=6.60
Number of Profiles= 1
Profile Names=P100yr
River Rch & RM=VallyRn,Main,15754
     909
River Rch & RM=VallyRn,Main,13152
    1120
River Rch & RM=VallyRn,Main,10160
    1270
River Rch & RM=VallyRn,Main,7789
    1420
Boundary for River Rch & Prof#=VallyRn,Main            , 1
Up Type= 0
Dn Type= 3
Dn Slope=0.013122
DSS Import GetInterval= 0
DSS Import GetPeak= 0
DSS Import FillOption= 0

--- VallyRn.g01 (geometry) ---

Geom Title=Geometry
Program Version=6.60

River Reach=VallyRn         ,Main
Reach XY= 30
      1643174.64       452949.12     1643390.042       453110.17
     1643482.368      453503.693     1643771.068      454015.255
      1643717.52        454669.2      1643409.36       455197.68
      1643333.04       455664.24       1643882.4       456391.44
1644213.38761092457107.264308385     1643968.051      457561.037
      1643802.75       458174.25 1644150.5835278458459.765379383
1644244.06859308458971.079152744      1644482.88        459111.6
      1644842.88       459828.72      1644579.36        460468.8
     1644273.562      460880.179     1644541.286      461633.126
     1644210.432       461963.52     1644096.615      461992.089
     1643914.138      461832.192      1643553.36       461841.84
        1643112.        461545.2      1642979.52        461581.2
      1642751.28       462346.56      1642836.96       463407.12
      1642916.88       463684.321643173.12716215463666.262288286
      1643397.84       464420.16     1643141.204      464890.432

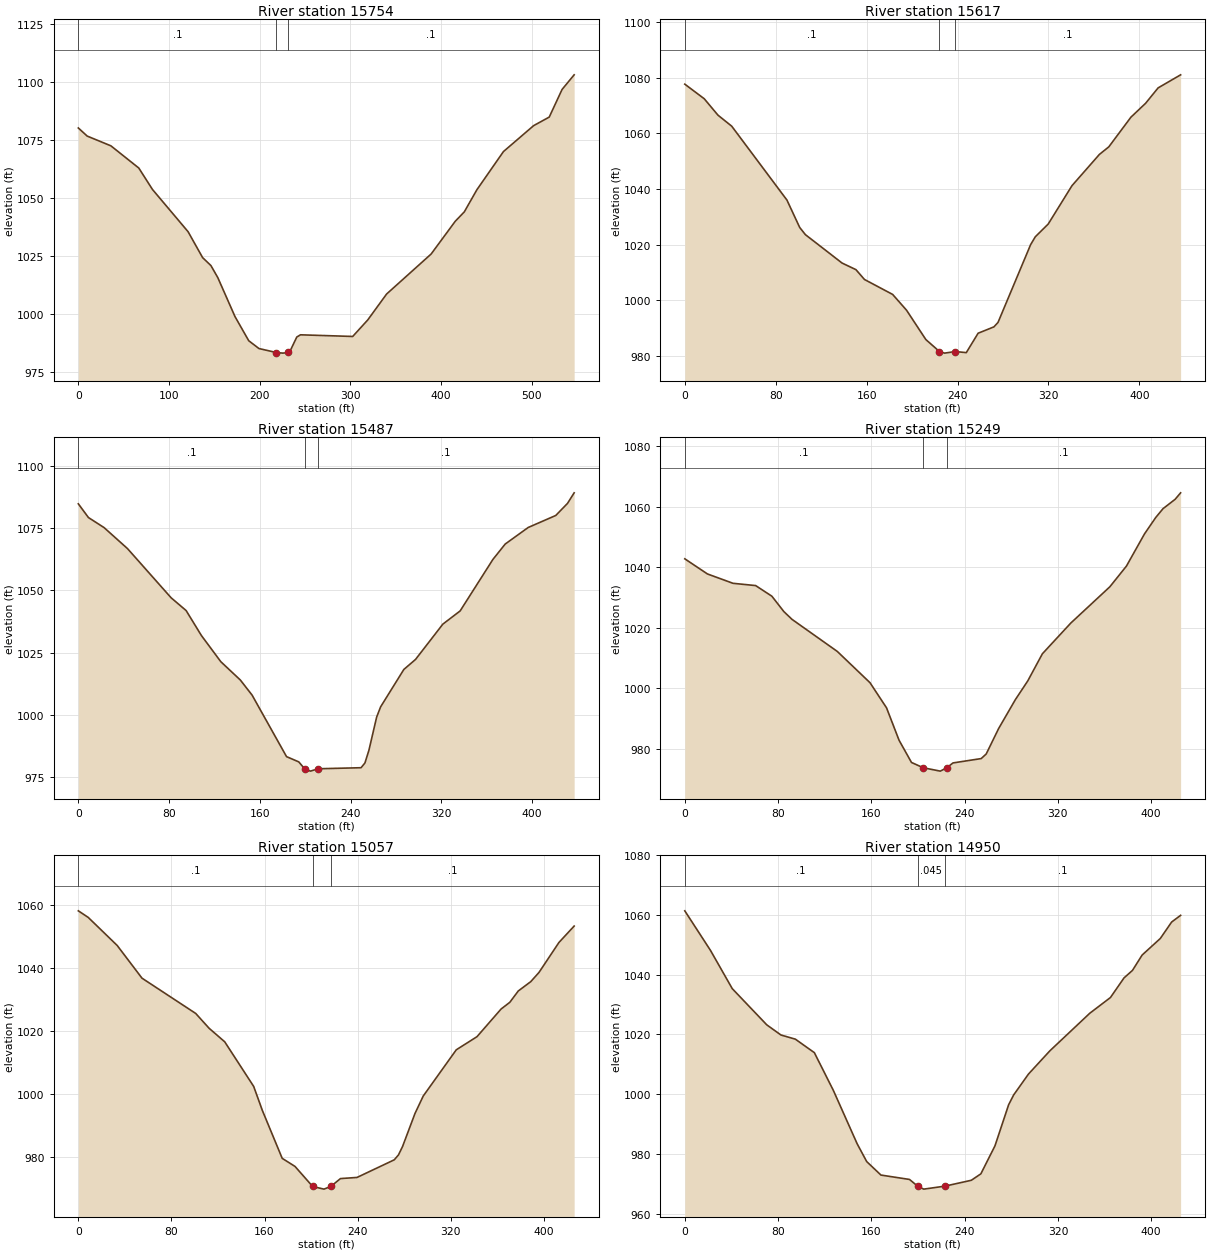
Type RM Length L Ch R = 1 ,15754   ,133.9,137.2,139.6
XS GIS Cut Line= 3
1643163.75072189453191.8271504781643314.29523233452931.528743954
1643557.18209868452890.507260318
#Sta/Elev= 30
       0  1080.3     9.8 1076.81    35.9 1072.62    66.7 1063.05    81.8 1053.81
   121.1 1035.61   137.1 1024.46   146.3 1021.02   153.9 1015.82   172.8  999.08
     188  988.65   199.3  985.28   218.3  983.58   225.7  983.31  231.58983.5815
   233.4  984.03     241  990.24   245.1   991.2   302.7  990.49   319.3  997.61
   340.1 1008.77   389.2    1026   415.8  1040.1   425.8 1044.16   439.7  1053.7
     469 1070.14   502.3 1081.31   519.5 1084.99   533.7 1096.92     547  1103.2
#Mann= 3, -1 ,  0
       0     0.1       0   218.3   0.045       0  231.58     0.1       0
Bank Sta=218.3,231.58
XS Rating Curve= 0 ,0
Exp/Cntr(USF)=0,0
Exp/Cntr=0.3,0.1

Type RM Length L Ch R = 1 ,15617   ,124.4,130.1,129.4
XS GIS Cut Line= 2
1643184.30931442453229.3821901381643538.05670531452974.052708527
#Sta/Elev= 30
       0 1077.68    17.1 1072.44    29.2 1066.54    41.3 1062.58    89.9 1036.04
   101.1 1026.22   106.1 1023.64   138.4 1013.43   150.6 1011.06   158.1 1007.53
   182.9 1002.16   195.1  996.51   212.1  985.96  224.11 981.651   228.6  981.08
     238  981.65   247.7  981.26   258.1  988.22     272  990.51   275.6  992.09
   304.3 1020.03   308.4 1022.85   319.8 1027.45   340.7 1041.22   364.8 1052.43
   373.1 1055.16   392.6 1065.83   405.5 1070.81   416.5 1076.34   436.3 1081.03
#Mann= 3, -1 ,  0
       0     0.1       0  224.11   0.045       0     238     0.1       0
Bank Sta=224.11,238
XS Rating Curve= 0 ,0
Exp/Cntr(USF)=0,0
Exp/Cntr=0.3,0.1

Type RM Length L Ch R = 1 ,15487   ,237.7,237.8,234.6
XS GIS Cut Line= 2
1643192.86890866453273.7361659521643610.56465846453145.412482258
#Sta/Elev= 30
       0 1084.79     8.9 1079.28    22.7 1075.23    43.3 1066.81    81.8 1047.01
      95 1041.89   108.5 1031.83   125.6 1021.32   142.8 1013.96   153.1 1007.93
   183.5  983.17   194.3  981.05  199.41978.3013   204.6  977.34   211.4  978.29
   249.2  978.71   252.6  980.62   256.1   985.7   262.9  999.02   266.4 1003.16
   286.9 1018.21   297.2 1022.24   321.3 1036.44   336.5 1041.73   365.4 1062.44
   376.2 1068.61   396.5 1075.28   420.8 1080.11   431.1 1084.94     437 1089.21
#Mann= 3, -1 ,  0
       0     0.1       0  199.41   0.045       0   211.4     0.1       0
Bank Sta=199.41,211.4
XS Rating Curve= 0 ,0
Exp/Cntr(USF)=0,0
Exp/Cntr=0.3,0.1

Type RM Length L Ch R = 1 ,15249   ,191.1,192.1,190.4
XS GIS Cut Line= 6
1643265.06077875453499.4817503391643348.36441793453471.815467089
1643418.27044609453444.5625688431643510.36704667453405.598736003
 1643579.4394151453376.3753692511643661.83754426453346.712042749
#Sta/Elev= 30
       0 1042.73    19.4 1037.73    41.4 1034.63    60.8 1033.88    74.7 1030.37
      85 1025.28      92 1022.71   130.8 1012.12   158.9 1001.77   173.1  993.45
   183.8  982.77   194.5  975.39  204.64973.6416   219.2  972.53  224.76973.6407
   230.1  975.24   254.3  976.68   258.6   978.2   269.3  986.64   283.6  996.16
   294.3 1002.39   306.8 1011.33   331.2  1021.5   364.7 1033.49   378.9 1040.32
   394.4 1050.96   404.1 1056.42   410.3 1059.31   420.7 1062.41   425.4 1064.55
#Mann= 3, -1 ,  0
       0     0.1       0  204.64   0.045       0  224.76     0.1       0
Bank Sta=204.64,224.76
XS Rating Curve= 0 ,0
Exp/Cntr(USF)=0,0
Exp/Cntr=0.3,0.1

Type RM Length L Ch R = 1 ,15057   ,108.6,106.8,104
XS GIS Cut Line= 2
1643334.66588261453676.867997256 1643727.9939855453512.918615936
#Sta/Elev= 30
       0 1058.24     8.5 1056.14    33.4 1047.21    54.7  1036.8   100.9 1025.56
   112.4 1020.84   125.8 1016.54   150.7 1002.33   158.1  994.73   175.2  979.43
   186.2  976.86  201.39 970.473   211.1  969.63   216.9  970.47   225.3  972.99
   239.5  973.35   271.5  978.96   275.1  980.51   278.6  983.17   289.3   993.7
   296.4  999.27   324.8 1013.99   342.6 1018.17   363.3 1026.97   370.8 1029.11
   378.1 1032.73   388.8 1035.69   395.9 1038.63     413 1048.15   426.1 1053.39
#Mann= 3, -1 ,  0
       0     0.1       0  201.39   0.045       0   216.9     0.1       0
Bank Sta=201.39,216.9
XS Rating Curve= 0 ,0
Exp/Cntr(USF)=0,0
Exp/Cntr=0.3,0.1

Type RM Length L Ch R = 1 ,14950   ,299.6,300,300.7
XS GIS Cut Line= 6
 1643410.6224955453813.6566469221643480.98751226453761.646580338
1643541.30038376453717.0669450911643621.71787384453657.627759501
1643683.52516492453615.0697737491643757.47547634453567.910747334
#Sta/Elev= 30
       0 1061.39      22 1048.16    40.7 1035.34    70.3 1023.22    82.5 1019.81
    94.8 1018.43   111.1 1013.91   127.4 1001.27   147.8  983.41     156  977.44
   168.2  972.93   192.7  971.46  199.65969.2228   204.9  968.22  223.13969.2231
   245.7  971.18   253.9  973.34     266  982.72   277.7  996.46     282  999.74
   294.7 1006.73   313.1 1014.53   347.3  1027.1     365 1032.36   376.7 1038.95
   383.9 1041.44   392.2 1046.59   407.8 1052.14   417.5 1057.64   425.2 1059.88
#Mann= 3, -1 ,  0
       0     0.1       0  199.65   0.045       0  223.13     0.1       0
Bank Sta=199.65,223.13
XS Rating Curve= 0 ,0
Exp/Cntr(USF)=0,0
Exp/Cntr=0.3,0.1

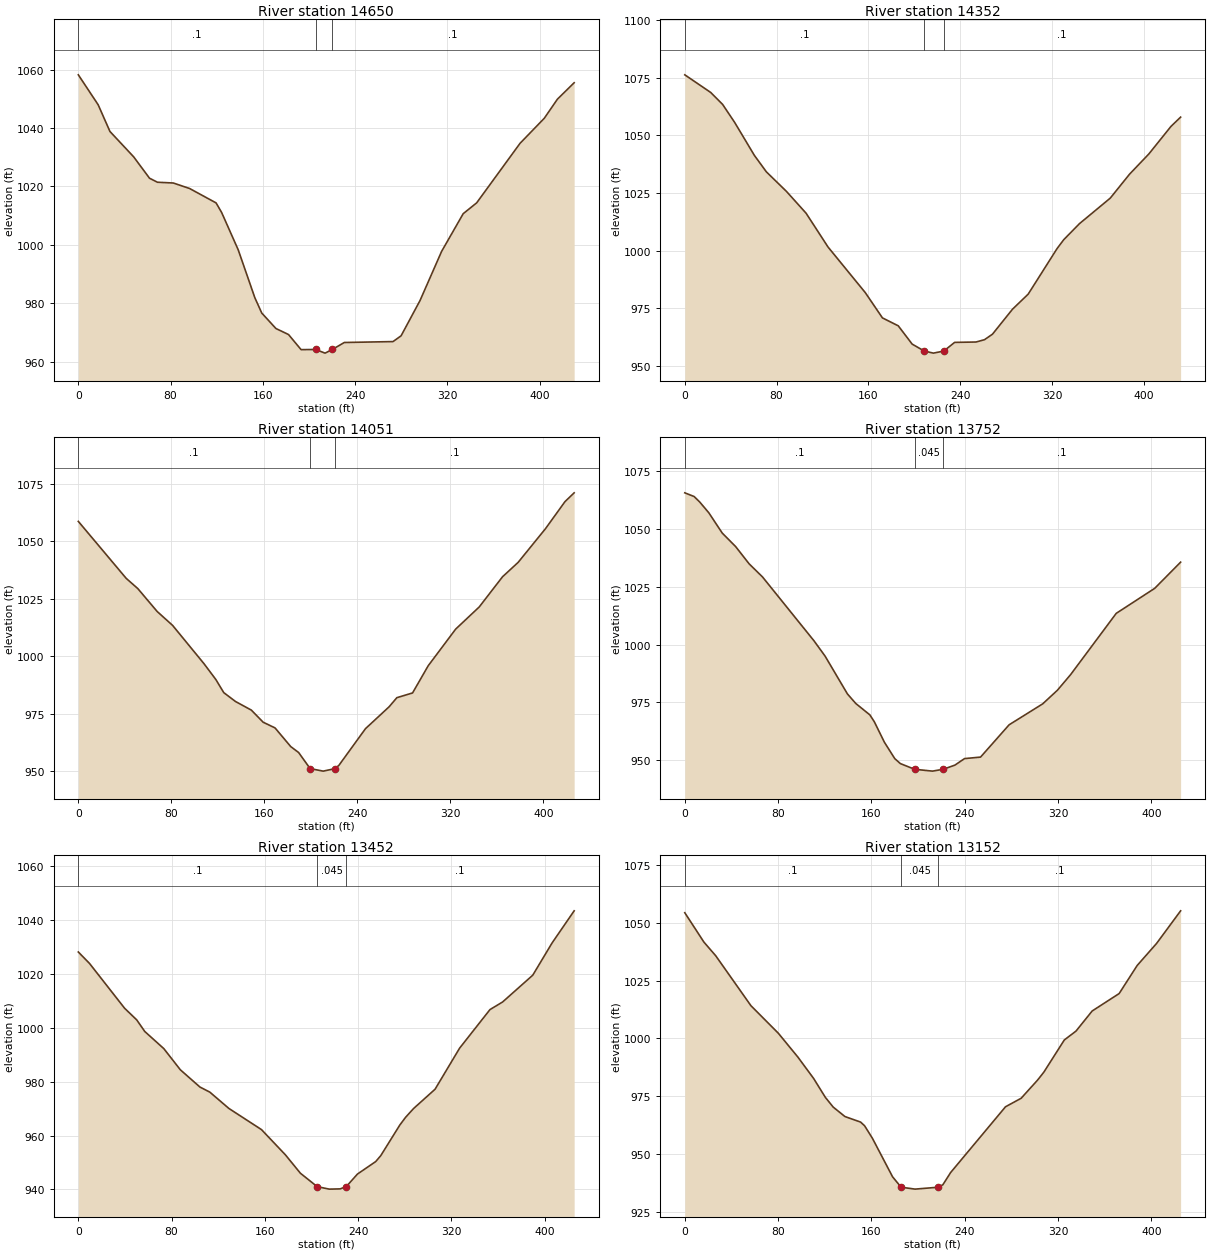
Type RM Length L Ch R = 1 ,14650   ,286.7,298.4,304.3
XS GIS Cut Line= 6
1643542.60582735454037.4734565021643630.50460167454010.932171002
1643695.86897226453973.1110524241643775.48495476453912.602643251
 1643835.1967776453867.2208442541643904.86100835453814.276068255
#Sta/Elev= 30
       0 1058.18    17.2 1047.93    27.4  1038.8      48  1030.1    61.7  1022.8
    68.6 1021.42    82.3 1021.16    96.4 1019.29   119.4 1014.35   124.2 1011.09
   138.6  998.29     153  981.91     159  976.66   171.3  971.36   182.2   969.3
   193.1  964.13   205.6  964.19   213.9  962.94   220.1  964.19   230.6  966.58
   272.8  966.89   279.8  968.88   296.2  980.94   314.9  997.75   333.6 1010.65
   345.3 1014.37   382.9 1034.74   403.9 1043.31   415.3 1049.85   429.8 1055.47
#Mann= 3, -1 ,  0
       0     0.1       0   205.6   0.045       0   220.1     0.1       0
Bank Sta=205.6,220.1
XS Rating Curve= 0 ,0
Exp/Cntr(USF)=0,0
Exp/Cntr=0.3,0.1

Type RM Length L Ch R = 1 ,14352   ,305.5,300.8,291.8
XS GIS Cut Line= 6
1643531.11569284454135.6235226691643614.42228475454164.206798837
1643682.27090234454196.3008947521643770.92951767454242.851654679
1643844.67805783 454266.646226511643934.12112042454284.530049011
#Sta/Elev= 30
       0 1076.28    22.6 1068.62      33 1063.42    43.4 1055.67    60.7 1041.28
    71.1 1034.18    88.5 1025.75   105.7 1016.23   124.8 1001.58   157.3  981.77
   172.2  970.84     186  967.39   198.1  959.46  208.71956.4445   216.6  955.55
  225.62956.4443   235.1  960.21   253.7  960.37   261.1  961.37   268.1  963.78
   285.5  974.59   299.2  981.15   324.4 1000.94   330.2 1004.78   343.9 1011.73
   370.7 1022.79   387.5 1033.18   404.3 1041.94   423.6 1053.91     432 1057.93
#Mann= 3, -1 ,  0
       0     0.1       0  208.71   0.045       0  225.62     0.1       0
Bank Sta=208.71,225.62
XS Rating Curve= 0 ,0
Exp/Cntr(USF)=0,0
Exp/Cntr=0.3,0.1

Type RM Length L Ch R = 1 ,14051   ,287.1,299.3,305.1
XS GIS Cut Line= 6
1643518.34997034454556.2220909151643605.95346968454541.919298008
1643678.69184126 454522.648995341643775.72839259454498.160199165
1643848.73349592454481.0972411781643934.18345626454462.411911085
#Sta/Elev= 30
       0 1058.67    41.2 1033.85    51.2 1029.39    67.8 1019.44    81.1 1013.37
   108.1   996.7   118.3   989.8   125.1   984.1   135.2  980.23   148.8  976.49
     159  971.21   169.2  968.73   182.7   960.6   189.5  958.01   199.4  951.01
   210.6  949.91  220.97951.0112   224.2  952.47     247   968.4   267.3  977.91
     274   981.9   287.5  983.96     301  995.83   324.6 1011.77   344.8 1021.38
   364.9 1034.56   378.3 1040.81   401.8 1055.47   418.6 1067.27   426.5 1071.11
#Mann= 3, -1 ,  0
       0     0.1       0   199.4   0.045       0  220.97     0.1       0
Bank Sta=199.4,220.97
XS Rating Curve= 0 ,0
Exp/Cntr(USF)=0,0
Exp/Cntr=0.3,0.1

Type RM Length L Ch R = 1 ,13752   ,299,300,303
XS GIS Cut Line= 6
1643469.26411051454679.335689843   1643544.12026454724.643670082
1643608.28253326454763.478894249  1643693.832559454815.259630591
1643758.34358484454853.5187404161643834.21252759454897.153167591
#Sta/Elev= 30
       0 1065.59       8 1063.99    12.8 1061.62    20.6 1056.96    32.1  1048.2
    43.6 1042.35    55.1 1034.93    66.6 1029.25   110.8 1001.61   120.3  994.99
   139.4  978.69   146.6  974.54   158.6  969.65   162.5  966.62   171.1  957.81
     180  950.72   184.8  948.58  196.99 946.132   212.3  945.33  221.49946.1318
   231.5  947.92   239.8  950.75   253.5  951.39     278  965.35   306.8  974.41
   319.4  980.29   330.7  987.03   369.8  1013.5   402.8 1024.32     425 1035.63
#Mann= 3, -1 ,  0
       0     0.1       0  196.99   0.045       0  221.49     0.1       0
Bank Sta=196.99,221.49
XS Rating Curve= 0 ,0
Exp/Cntr(USF)=0,0
Exp/Cntr=0.3,0.1

Type RM Length L Ch R = 1 ,13452   ,308,300,294.1
XS GIS Cut Line= 6
 1643345.0478235 454908.060626091643411.68220468454964.771470666
1643468.79757601455013.3806254271643544.95129509455078.192503676
1643602.84816092455125.8833531741643672.47334975455179.300897256
#Sta/Elev= 30
       0 1028.08     9.6 1023.83    39.7 1007.21    50.1 1002.89      57  998.59
    73.3  992.25    87.5  984.39   104.3  977.99   112.8   976.1   129.2  970.03
   157.1   962.2   177.6  952.85   190.5  946.01  204.92941.0326   215.3  940.12
   224.6  940.21  229.78 941.033   239.4   945.7   255.1  950.35   259.4  952.53
   275.8  963.92   280.7  966.75   287.5  969.99     306  977.18   327.1  992.44
   353.1 1006.72   363.9 1009.53   389.8 1019.48   406.3 1031.39   425.3 1043.35
#Mann= 3, -1 ,  0
       0     0.1       0  204.92   0.045       0  229.78     0.1       0
Bank Sta=204.92,229.78
XS Rating Curve= 0 ,0
Exp/Cntr(USF)=0,0
Exp/Cntr=0.3,0.1

Type RM Length L Ch R = 1 ,13152   ,302.9,300,298.9
XS GIS Cut Line= 6
 1643175.5169946 455267.725917251643261.03257158455286.254423499
1643334.33163759455302.1362815051643432.06372559 455323.31209217
1643505.36311968455339.1939501761643590.87869668455357.722784504
#Sta/Elev= 30
       0 1054.34    16.4 1041.63    26.5 1035.74    56.7 1014.13    80.2 1002.21
      97  991.87   110.4  982.69   120.5  974.48   127.2  970.29   137.3  966.19
   150.7   963.8   154.1  962.22   160.8  956.82   178.1  940.14  185.41935.6382
   197.4  934.81  217.23935.6392   221.2   936.7   227.9  942.01   274.9  970.42
   288.3   974.1   302.3  981.91   307.8  985.42   325.3  999.31   335.3 1003.14
   349.2 1011.85   372.3 1019.38   387.8 1031.55   404.4 1041.06     425 1055.16
#Mann= 3, -1 ,  0
       0     0.1       0  185.41   0.045       0  217.23     0.1       0
Bank Sta=185.41,217.23
XS Rating Curve= 0 ,0
Exp/Cntr(USF)=0,0
Exp/Cntr=0.3,0.1

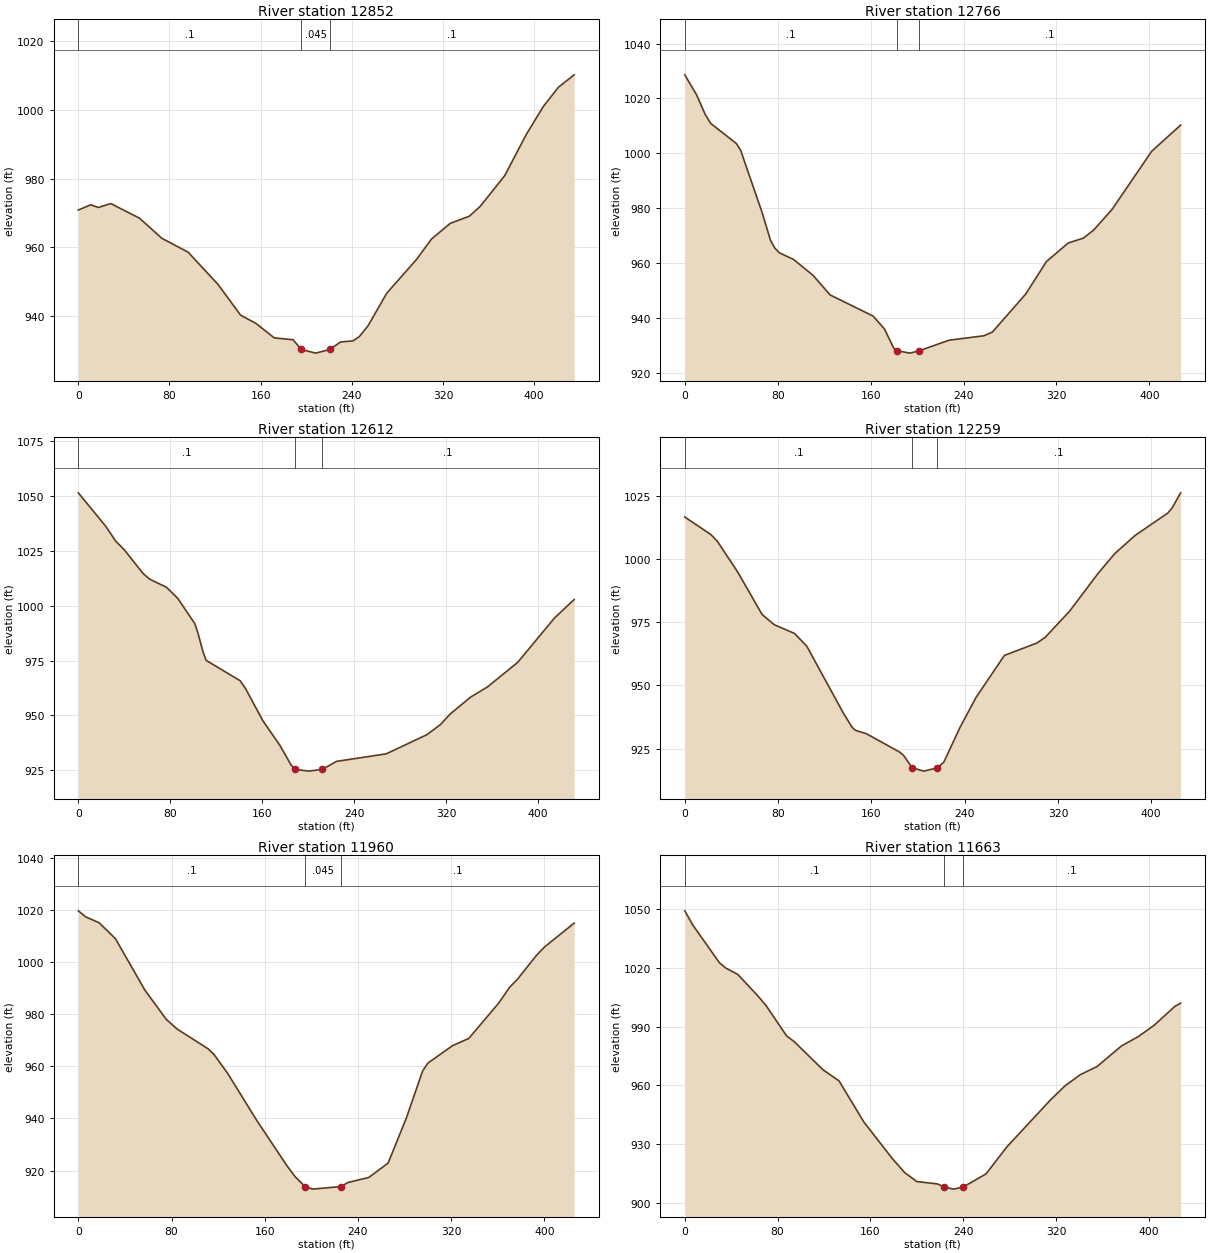
Type RM Length L Ch R = 1 ,12852   ,91.7,85.7,79.9
XS GIS Cut Line= 6
1643121.64866401455593.9992148431643208.96312192455599.693757251
1643283.80417959455604.5736687631643383.59236585455611.080873594
1643458.89831759455608.288228258 1643552.1835641 455580.68362467
#Sta/Elev= 30
       0  970.85    10.9  972.36    17.5  971.59    28.5  972.72    53.6  968.48
    73.4  962.59    96.4  958.56   122.7  949.14   142.4  940.23   155.6   937.9
     172  933.62   188.4  933.09  195.64930.2626   208.2  929.19  220.81930.2624
     230  932.42     241  932.76   246.6  934.02   254.2  937.13   270.6  946.61
   296.9  956.51     310  962.43   326.4  966.96   343.1  969.04   352.8  971.96
   374.2  980.86   393.1  992.84   408.2 1001.06   421.4 1006.61   435.1 1010.19
#Mann= 3, -1 ,  0
       0     0.1       0  195.64   0.045       0  220.81     0.1       0
Bank Sta=195.64,220.81
XS Rating Curve= 0 ,0
Exp/Cntr(USF)=0,0
Exp/Cntr=0.3,0.1

Type RM Length L Ch R = 1 ,12766   ,155.7,154.1,150.6
XS GIS Cut Line= 2
1643174.61702131455775.229778559 1643557.1470083455585.821726746
#Sta/Elev= 30
       0 1028.58    10.3 1021.16    17.6 1014.12    22.4 1010.84    44.5  1003.5
    48.2 1000.93    66.5  978.45    73.8  968.24    77.5  965.41    81.5  963.65
    93.5  961.31   110.4  955.48   125.1  948.32   162.1  940.62   171.9  935.92
     180  928.84  182.43927.9929   193.9   927.1     202  927.99   227.6  931.82
   257.6  933.43   264.9  934.81   293.5  948.63   311.4   960.5   330.1  967.25
   343.3  969.06   352.1  972.01   367.8  979.46     402 1000.72   426.9 1010.24
#Mann= 3, -1 ,  0
       0     0.1       0  182.43   0.045       0     202     0.1       0
Bank Sta=182.43,202
XS Rating Curve= 0 ,0
Exp/Cntr(USF)=0,0
Exp/Cntr=0.3,0.1

Type RM Length L Ch R = 1 ,12612   ,345,352.7,354.5
XS GIS Cut Line= 2
1643297.63100768455937.7324592031643619.58144501455650.647371866
#Sta/Elev= 30
       0 1051.53    23.8 1036.31    32.3 1029.63      40 1025.51    56.3 1014.74
    61.9 1012.17    76.7 1008.42    86.5 1003.36   101.3  991.87   104.1  987.48
   108.5  978.89   111.2  975.07   140.8  965.77   145.7     962   160.5  947.56
   175.3  936.34   185.1  927.34   188.8  925.31   200.4  924.51  212.29 925.298
   224.6  928.96   267.8  932.38   303.5   941.2   315.1  945.77   323.5  950.57
   341.4  958.33   356.1  962.98   382.3  974.17   414.2  994.33   431.4 1002.84
#Mann= 3, -1 ,  0
       0     0.1       0   188.8   0.045       0  212.29     0.1       0
Bank Sta=188.8,212.29
XS Rating Curve= 0 ,0
Exp/Cntr(USF)=0,0
Exp/Cntr=0.3,0.1

Type RM Length L Ch R = 1 ,12259   ,308.6,299.2,293.5
XS GIS Cut Line= 6
1643454.07483642456138.4489133361643536.30039376456108.426007509
1643607.45149818456084.7082071751643702.32007484456053.085895091
1643772.77236176456027.272298425  1643854.544836455995.890471429
#Sta/Elev= 30
       0 1016.58    22.3 1009.66    27.9    1007    45.3  994.88    66.3  978.03
    76.8  973.96    94.1  970.54   104.6  965.51   135.7  939.28   143.3  933.55
   146.1  932.28   155.9  930.85   184.1  923.68   187.6  922.34  195.03 917.411
   204.9   916.1  216.67917.4108   222.2  919.72     236  933.37   249.8  945.27
   274.1  961.86   302.1  966.78   309.1  969.01   330.1  979.41   354.6  994.39
   368.7 1002.09   386.2  1009.3   414.3 1018.17   418.1 1020.29   425.2 1026.14
#Mann= 3, -1 ,  0
       0     0.1       0  195.03   0.045       0  216.67     0.1       0
Bank Sta=195.03,216.67
XS Rating Curve= 0 ,0
Exp/Cntr(USF)=0,0
Exp/Cntr=0.3,0.1

Type RM Length L Ch R = 1 ,11960   ,289.2,297,302.3
XS GIS Cut Line= 6
1643651.44747317456478.4410155121643713.22261208456415.994618088
1643765.50137892456361.9071278421643830.44941175456285.853802249
1643878.26690142456228.074062169 1643935.1591761456161.579116419
#Sta/Elev= 30
       0 1019.62     6.3 1017.32    17.9 1015.03    31.9 1008.91    57.1  989.22
    75.5  977.99    84.8  974.28   111.4  966.71   116.5  964.51   128.1  957.34
   153.2  939.22   179.1  921.85   186.1  917.66  194.58913.8946   201.2  912.89
  225.63913.8939   231.4  915.44   249.3  917.36   265.9  922.88   281.6  940.19
   295.5  958.16     300  961.23   321.2   967.9   335.2   970.7   360.8  984.22
   370.1  990.23   377.2  993.52   393.3 1002.58   400.3 1005.81   425.6  1014.9
#Mann= 3, -1 ,  0
       0     0.1       0  194.58   0.045       0  225.63     0.1       0
Bank Sta=194.58,225.63
XS Rating Curve= 0 ,0
Exp/Cntr(USF)=0,0
Exp/Cntr=0.3,0.1

Type RM Length L Ch R = 1 ,11663   ,167.2,168.5,167.4
XS GIS Cut Line= 6
1643723.06970526456651.8812854291643804.88187759456620.849195257
1643875.00673734456594.2498390081643968.20799451456557.996630669
1644038.02642442456530.024901837 1644121.3595911456496.708695501
#Sta/Elev= 30
       0 1049.11       7 1041.78    29.9  1022.6    35.1    1020    45.6 1016.72
    63.2 1005.57    70.2 1000.68    87.7  985.36    94.7  982.16   119.3  967.95
   132.9  962.41   154.4  941.37     179  922.65   189.6  915.55   200.1  910.97
   217.7  909.79  223.72908.1768   231.8  907.12  239.93908.1779   259.7  914.87
   277.6  928.61   315.2  952.57   327.8   959.8   341.2  965.59   355.4  969.65
   376.6  980.21   390.7  984.83   404.8  990.77   422.5 1000.35   427.5 1002.03
#Mann= 3, -1 ,  0
       0     0.1       0  223.72   0.045       0  239.93     0.1       0
Bank Sta=223.72,239.93
XS Rating Curve= 0 ,0
Exp/Cntr(USF)=0,0
Exp/Cntr=0.3,0.1

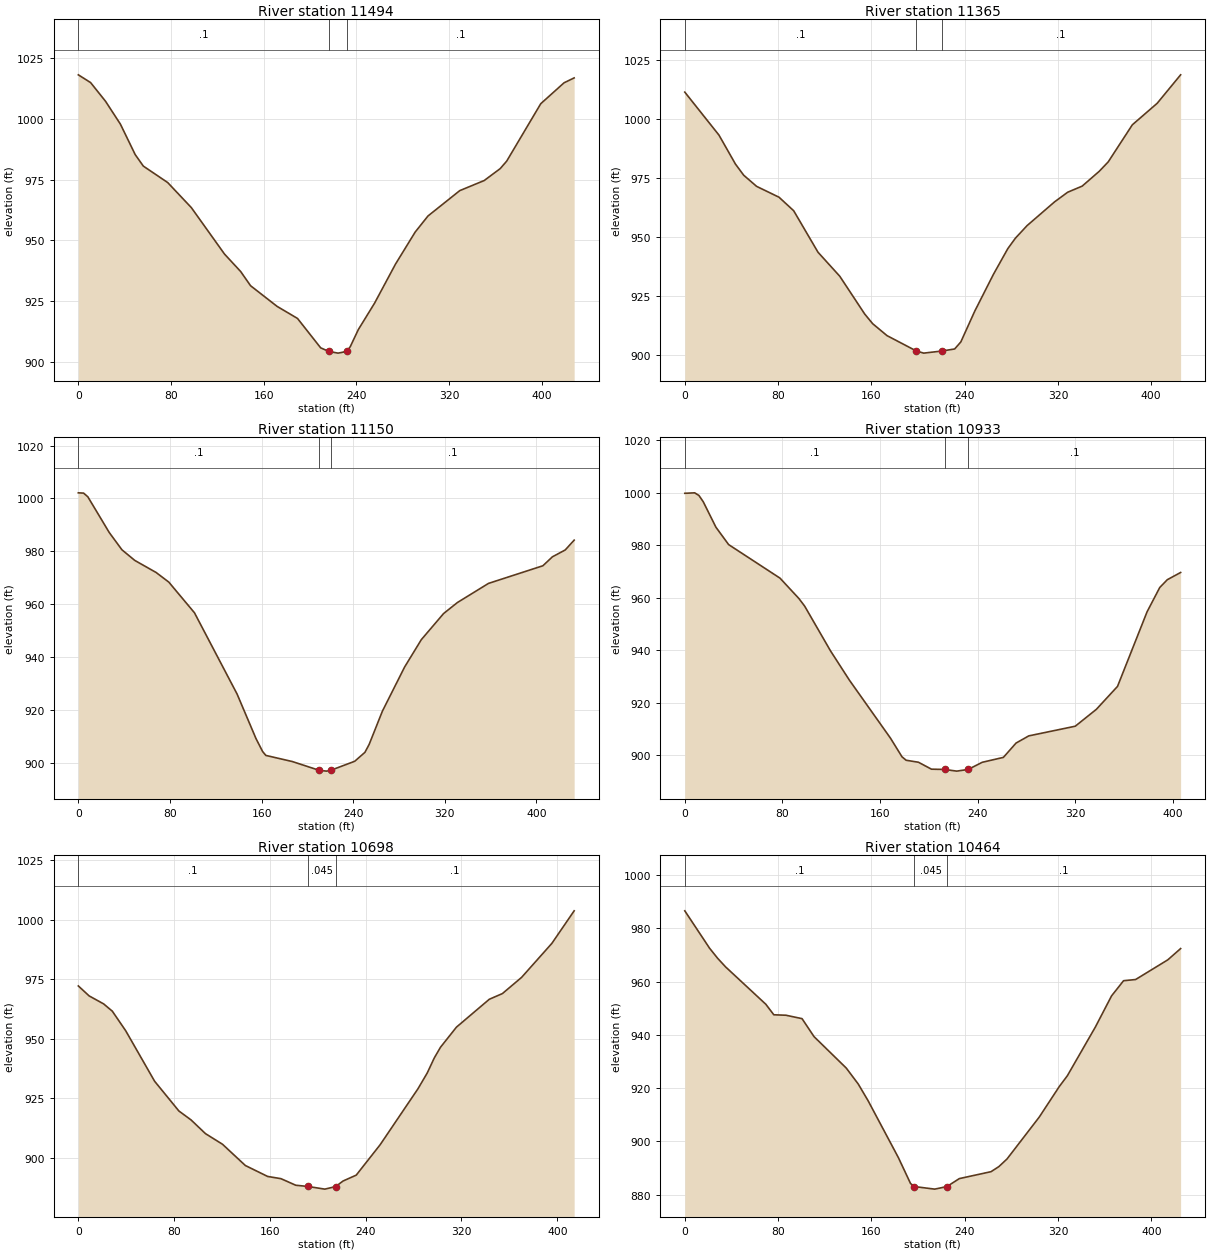
Type RM Length L Ch R = 1 ,11494   ,132.7,129.5,127.5
XS GIS Cut Line= 2
1643801.67204291456796.0126553991644202.77144675456647.271626474
#Sta/Elev= 30
       0 1018.09    10.6 1014.89    23.5 1007.18    36.3  997.79    49.1  985.23
    56.1  980.51    77.1  973.75    97.5  963.43   126.1  944.32   140.1   937.1
   148.6  931.28   171.5  922.77   189.1  917.81   209.1   905.7   216.2  904.22
   224.1  903.53  231.55 904.215   234.6  906.17   241.6  913.23   255.6   924.1
   273.6  940.13   290.6  953.34   301.7  959.99   329.1  970.42   350.2  974.58
     364  979.48   369.6  982.57     399 1006.21   419.1 1014.81   427.8 1016.82
#Mann= 3, -1 ,  0
       0     0.1       0   216.2   0.045       0  231.55     0.1       0
Bank Sta=216.2,231.55
XS Rating Curve= 0 ,0
Exp/Cntr(USF)=0,0
Exp/Cntr=0.3,0.1

Type RM Length L Ch R = 1 ,11365   ,213.3,215.1,216.1
XS GIS Cut Line= 6
1643888.86891434456956.0716219251643960.97277276456906.500526845
1644022.77579875456864.0104543421644105.17983343  456807.3576805
1644166.98285942 456764.867936091644242.32850926456720.012054667
#Sta/Elev= 30
       0 1011.41    29.3  993.18    43.4  980.92    50.5  976.16    61.6  971.42
    80.8  966.82    93.4  961.07   114.2   943.5   132.9  933.29   154.3  917.25
   161.1  913.16   173.4   908.1  198.65901.5561   204.9  900.67   220.4  901.56
   231.4  902.43   236.7  905.41   248.7  918.52   264.6  934.03     277     945
   283.5  949.43   293.5  954.76   317.1  964.85   328.3  968.92   340.8  971.54
   355.4  977.81   363.1   981.8   383.8  997.55   405.1 1006.67   425.2 1018.75
#Mann= 3, -1 ,  0
       0     0.1       0  198.65   0.045       0   220.4     0.1       0
Bank Sta=198.65,220.4
XS Rating Curve= 0 ,0
Exp/Cntr(USF)=0,0
Exp/Cntr=0.3,0.1

Type RM Length L Ch R = 1 ,11150   ,210.8,216.9,222.3
XS GIS Cut Line= 2
1643971.60595359457127.8321051751644353.35459566456923.636487993
#Sta/Elev= 30
       0  1002.1     4.6 1001.99     8.3  1000.6      27  987.07    38.1  980.52
    49.3  976.51    67.9  971.95      79   968.3   101.4  956.69   138.6  925.94
   155.1  909.09   160.9  904.17   163.7   902.7   186.9  900.37  210.28 897.058
   216.7  896.75   220.4  897.06   241.3  900.48   250.2  903.85   253.9  906.85
   265.5  919.47   284.9  936.18   299.5  946.54   318.9   956.4     331  960.58
   358.1  967.81   405.6  974.49   413.9  977.87   425.1  980.47   432.9  984.19
#Mann= 3, -1 ,  0
       0     0.1       0  210.28   0.045       0   220.4     0.1       0
Bank Sta=210.28,220.4
XS Rating Curve= 0 ,0
Exp/Cntr(USF)=0,0
Exp/Cntr=0.3,0.1

Type RM Length L Ch R = 1 ,10933   ,233.7,235.3,236.8
XS GIS Cut Line= 2
1643961.36902777457147.2944403831644346.16861016457277.280358295
#Sta/Elev= 30
       0  999.81     8.1  999.99    11.6  998.97    15.1   996.6    25.5  986.88
    35.9  980.25      78  967.45    93.5  959.67    98.2  956.78   119.4  939.69
   134.9  928.51   168.6  906.36   177.9  899.34   181.3     898   191.4  897.24
   202.1  894.59   212.9  894.49   222.8  893.85   232.1894.4863   243.7  897.22
     261  899.09   271.4  904.56   281.8  907.29   319.9  910.98   337.2  917.43
   354.5  926.16   378.7  954.59   389.1  963.88   395.3  966.86   406.2  969.61
#Mann= 3, -1 ,  0
       0     0.1       0   212.9   0.045       0   232.1     0.1       0
Bank Sta=212.9,232.1
XS Rating Curve= 0 ,0
Exp/Cntr(USF)=0,0
Exp/Cntr=0.3,0.1

Type RM Length L Ch R = 1 ,10698   ,236.4,233.1,230.9
XS GIS Cut Line= 2
1643894.68339094457336.7844142341644261.58628442457528.701578988
#Sta/Elev= 30
       0  972.16       9  967.99    21.1  964.64    28.4  961.57    39.6  953.34
    63.7   932.2      84  919.71    94.1  915.99   106.2  910.22   120.4  905.77
   139.5  896.85   158.1  892.27   169.2  891.34   181.6  888.58   191.4  888.09
   205.9  886.95  215.06888.0445     221  890.33   232.1  892.82   252.1  905.59
   283.7  929.07   291.4  935.66   297.3  941.98   302.5  946.47   315.8  954.88
   343.2  966.56   354.2  968.96   370.2  975.75   395.5  990.02   414.1 1003.66
#Mann= 3, -1 ,  0
       0     0.1       0   191.4   0.045       0  215.06     0.1       0
Bank Sta=191.4,215.06
XS Rating Curve= 0 ,0
Exp/Cntr(USF)=0,0
Exp/Cntr=0.3,0.1

Type RM Length L Ch R = 1 ,10464   ,306.1,304.3,301.3
XS GIS Cut Line= 6
1643745.51454225457556.4404999171643828.83032051457583.175354585
 1643900.2435635 457606.090663091643995.46154892457636.644407749
1644066.87512001457659.5597162541644150.19089825457686.294242844
#Sta/Elev= 30
       0  986.56    21.2  972.55    28.1  968.77      35   965.5    69.5  951.47
    76.3  947.54    86.7  947.37   100.5  946.09   110.8  939.33   138.4  927.54
   148.7  921.53   157.1   915.3   183.1  893.91   193.5  884.21  196.82883.0578
   214.2   882.1  224.68883.0593   235.3  886.05   262.5  888.65   269.2  890.55
   276.2  893.42   303.8  909.13     321  920.61   327.9  924.65     352     943
   365.8  954.63   376.1  960.33   386.4  960.77     414  968.16     425  972.39
#Mann= 3, -1 ,  0
       0     0.1       0  196.82   0.045       0  224.68     0.1       0
Bank Sta=196.82,224.68
XS Rating Curve= 0 ,0
Exp/Cntr(USF)=0,0
Exp/Cntr=0.3,0.1

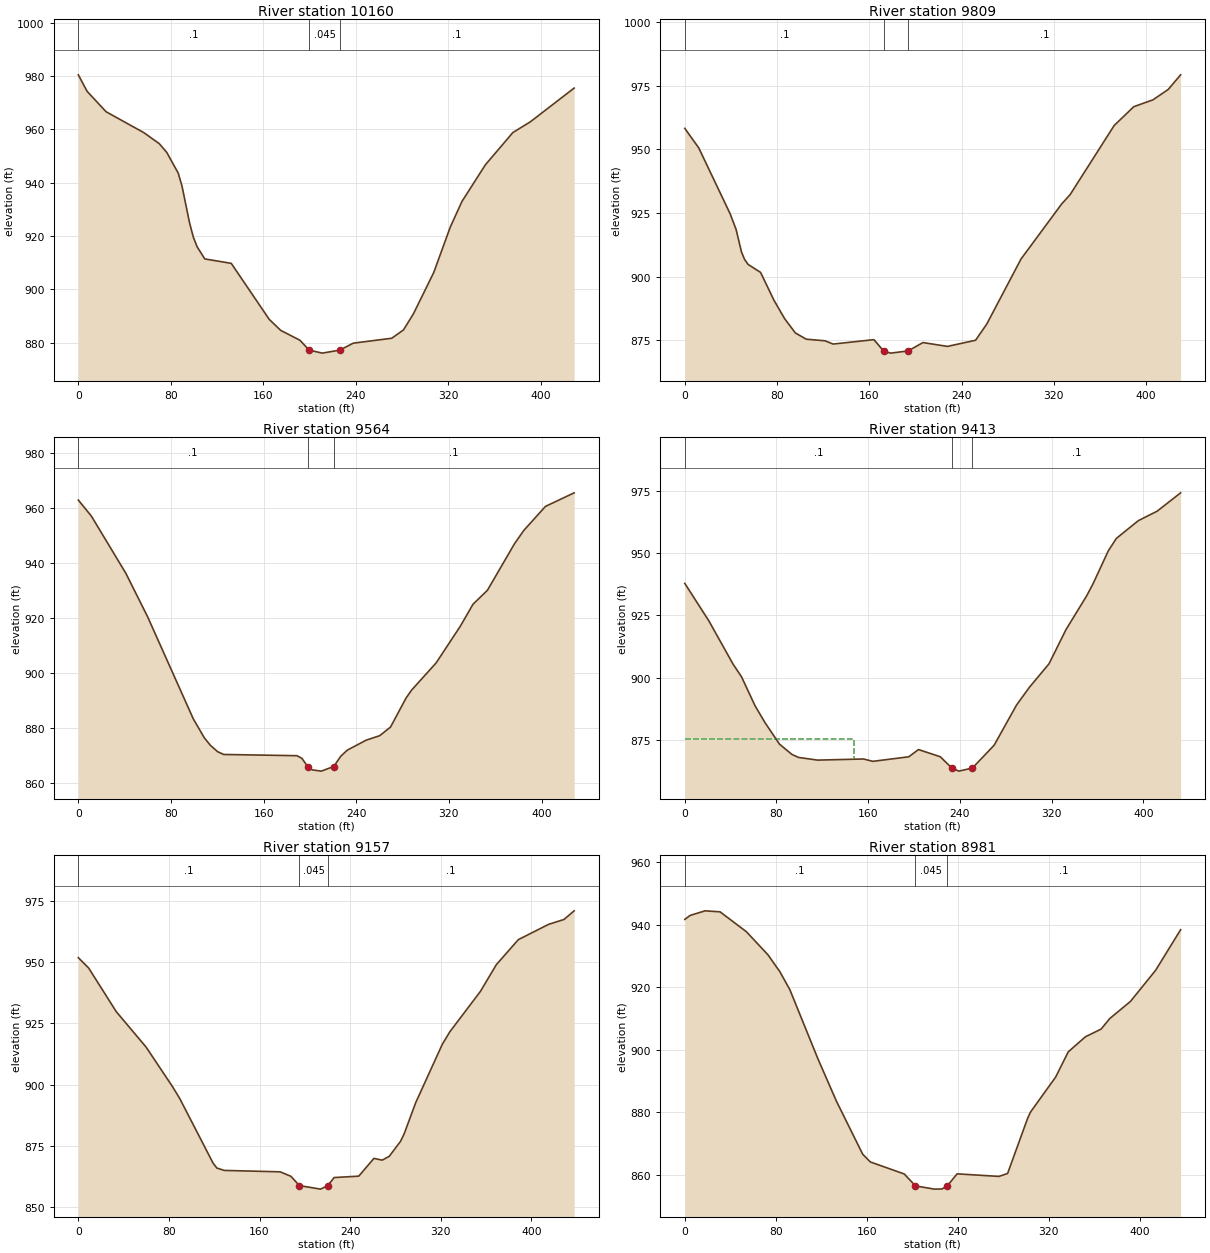
Type RM Length L Ch R = 1 ,10160   ,363.6,351.1,346.8
XS GIS Cut Line= 6
1643630.20014034457892.1228994281643717.63041167457895.620267749
1643792.57022242457898.6176370831643892.14548258457911.241627589
1643966.72472976 457929.046382011644053.15894009457951.983015925
#Sta/Elev= 30
       0   980.4     7.6  974.21      24  966.58    56.8  958.71      70  954.63
    76.5  951.35    86.4  943.61    89.7  938.74    96.2  925.03    99.5   919.6
   102.8  915.98   109.4  911.44   132.3  909.78   165.2  888.79   175.1  884.67
   191.7  880.99  199.73877.2828   211.1  876.15  226.22877.2827   237.9  879.88
   271.2  881.73   281.3  884.83   289.9  890.84   307.5  906.34   321.8  923.35
   331.9  932.95   352.2   946.7     376  958.79   391.1   962.8     429  975.44
#Mann= 3, -1 ,  0
       0     0.1       0  199.73   0.045       0  226.22     0.1       0
Bank Sta=199.73,226.22
XS Rating Curve= 0 ,0
Exp/Cntr(USF)=0,0
Exp/Cntr=0.3,0.1

Type RM Length L Ch R = 1 ,9809    ,243.3,244.6,244.9
XS GIS Cut Line= 2
1643698.28201723 458359.178642411644029.91843802 458085.68343094
#Sta/Elev= 30
       0  958.21    12.1  950.54    39.3  924.69    44.5   918.5    49.1  909.75
    51.7  906.85    54.8  904.82    65.7  901.66    77.3  890.74    86.6  883.46
    95.9  877.87   105.3  875.43   121.6   874.8   128.6  873.52     164  875.25
   172.5  870.72   178.5  869.96   193.7  870.83   206.5  874.11   227.7   872.6
   252.1  875.01   261.8  881.35   291.5   906.9   326.7  928.49   334.1   932.2
   372.3  959.34   389.3  966.72   405.9  969.41   419.1  973.47   429.9  979.23
#Mann= 3, -1 ,  0
       0     0.1       0   172.5   0.045       0   193.7     0.1       0
Bank Sta=172.5,193.7
XS Rating Curve= 0 ,0
Exp/Cntr(USF)=0,0
Exp/Cntr=0.3,0.1

Type RM Length L Ch R = 1 ,9564    ,150.1,151.7,150.8
XS GIS Cut Line= 6
1643861.93196034458520.9211824981643929.73727092458465.614534587
1643988.08229859458418.4883165061644065.87610626458355.654452667
1644118.24148709458301.421949595   1644172.18987458229.043813512
#Sta/Elev= 30
       0   962.8    11.3  956.95      41  936.21    59.7   920.5    99.3  883.26
   108.7  876.46   113.9  873.71   120.3  871.34   125.5  870.33   188.7  869.88
     193  868.95  198.07865.9484     202  864.73   209.8  864.27  220.57865.9487
   226.7  869.71   232.3   871.9   248.6  875.53   260.3  877.16   269.6  880.29
   283.2  890.95   287.8  893.72     309  903.61   329.9  916.95   340.9  924.96
   353.3  930.01   376.7  946.94   384.8   951.8   403.4  960.49   428.2  965.43
#Mann= 3, -1 ,  0
       0     0.1       0  198.07   0.045       0  220.57     0.1       0
Bank Sta=198.07,220.57
XS Rating Curve= 0 ,0
Exp/Cntr(USF)=0,0
Exp/Cntr=0.3,0.1

Type RM Length L Ch R = 1 ,9413    ,256.2,256.3,251.8
XS GIS Cut Line= 2
1643946.61823822458593.3680367631644308.72186669458356.607971996
#Sta/Elev= 30
       0  937.81      21  922.78      42  905.51    49.5  900.32    61.3   888.7
      70  881.93    82.6  873.32    93.5  869.17    99.2  867.98   115.8   866.9
   155.9  867.35   164.1  866.41   195.4  868.23   203.9  871.14   222.9  868.25
  233.03863.7046   239.1  862.48   250.9  863.71   269.9  872.88   289.5  889.04
   300.7  896.14   317.8  905.57   332.6  919.28   350.5  932.72   356.2  937.67
   369.4  950.79   376.5  955.85   395.7  962.99   412.1  966.79   432.6  974.16
#Mann= 3, -1 ,  0
       0     0.1       0  233.03   0.045       0   250.9     0.1       0
#XS Ineff= 2 , 0
          147.65  875.25
Permanent Ineff=
       F       F
Bank Sta=233.03,250.9
XS Rating Curve= 0 ,0
Exp/Cntr(USF)=0,0
Exp/Cntr=0.3,0.1

Type RM Length L Ch R = 1 ,9157    ,168.8,175.7,181.6
XS GIS Cut Line= 4
1643981.64117965 458705.636293111644167.34323329458718.946845989
1644205.21534008 458689.609298481644404.46263321458647.219503746
#Sta/Elev= 30
       0  951.73     9.1  947.52    33.5  929.72    59.8   915.3    82.8  899.41
    89.4  894.44     119  867.97   122.3  865.98   128.9  865.01   178.2  864.43
   187.7  862.61  195.17 858.824   213.9  857.38  220.26858.8234   225.9   862.1
   247.6  862.67     261  869.91   268.3   869.2   274.5  870.75   284.5  876.86
   287.7  879.93   297.9  892.63   321.4  916.44   328.1  921.56     355  937.96
   369.1  948.88   388.5  959.07   415.3  965.32   428.8  967.29   437.8  970.82
#Mann= 3, -1 ,  0
       0     0.1       0  195.17   0.045       0  220.26     0.1       0
Bank Sta=195.17,220.26
XS Rating Curve= 0 ,0
Exp/Cntr(USF)=0,0
Exp/Cntr=0.3,0.1

Type RM Length L Ch R = 1 ,8981    ,142.9,139,130.2
XS GIS Cut Line= 6
1644016.98512793 458895.82692875 1644104.2982735458888.021170095
1644178.71840025458878.5510446731644277.59812376458863.625549585
1644349.91917334458834.8841372581644435.00857009 458791.65784575
#Sta/Elev= 30
       0   941.7     4.7  942.98    17.8  944.45      31  944.13    54.1  937.78
    73.1  930.38    83.7  924.89    92.4  919.18   116.8  897.28   133.3  883.51
   156.4  866.53   163.1  864.05   192.9  860.21  202.75856.3937   219.5  855.35
   226.1   855.4  230.78856.3956   239.4  860.24   276.2  859.42   283.8  860.37
   301.4  878.03     304  880.06   326.1  891.26   337.1   899.3   352.2  904.12
     366  906.59   373.6  909.96   391.8  915.45   413.9   925.4   435.9   938.4
#Mann= 3, -1 ,  0
       0     0.1       0  202.75   0.045       0  230.78     0.1       0
Bank Sta=202.75,230.78
XS Rating Curve= 0 ,0
Exp/Cntr(USF)=0,0
Exp/Cntr=0.3,0.1