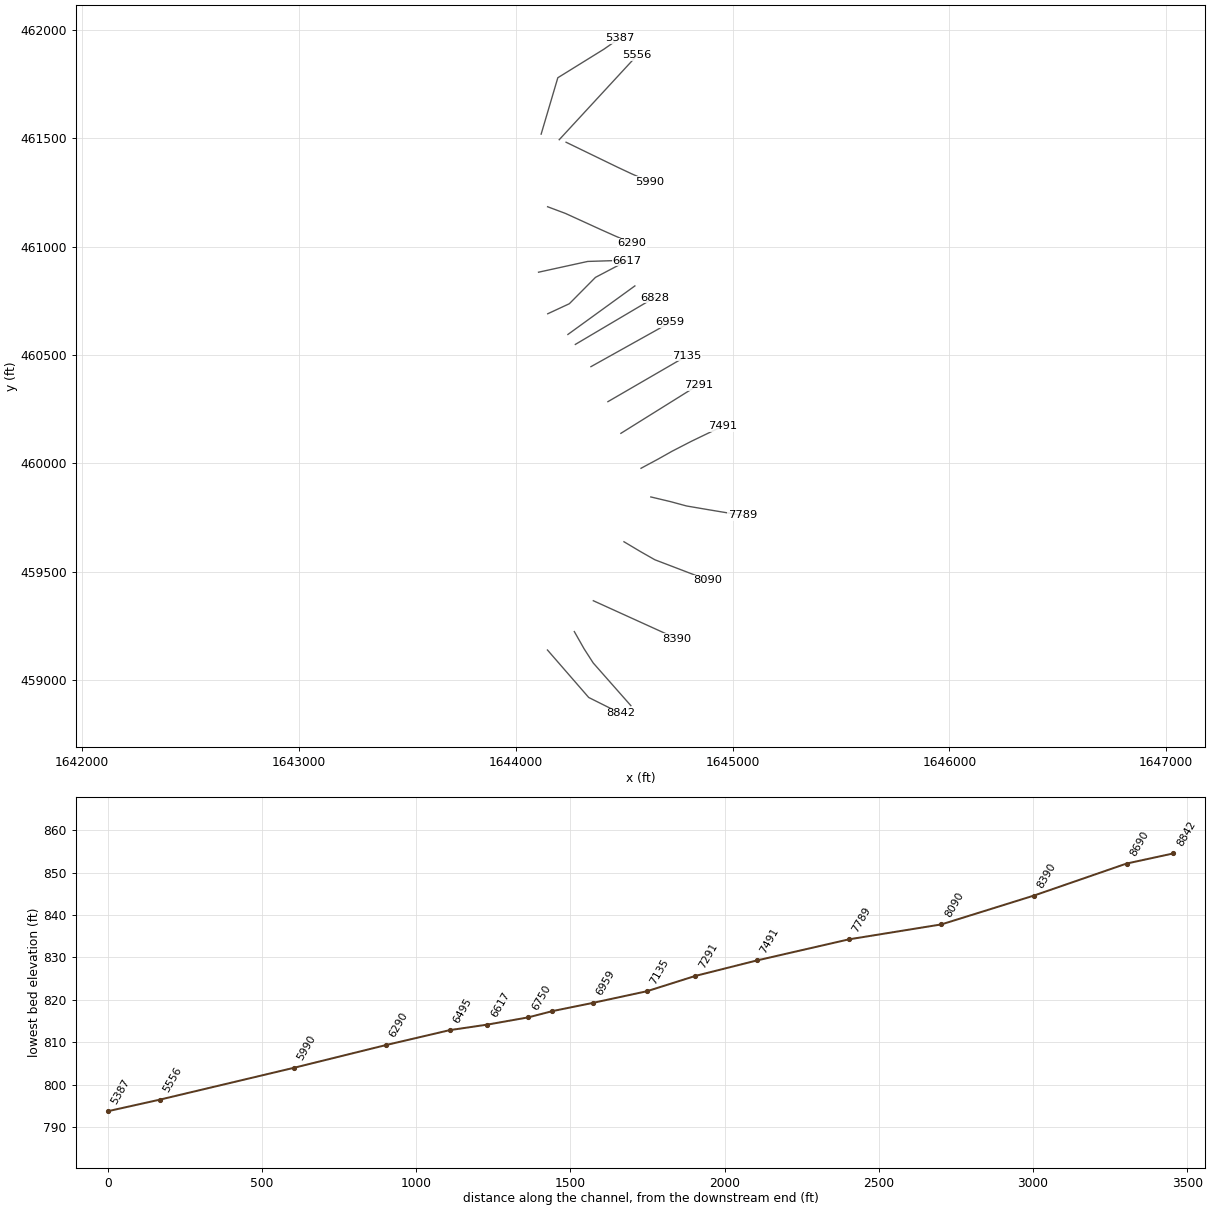
HEC-RAS study VallyRn.prj: VallyRn

--- VallyRn.g01 (geometry) --- (continued)

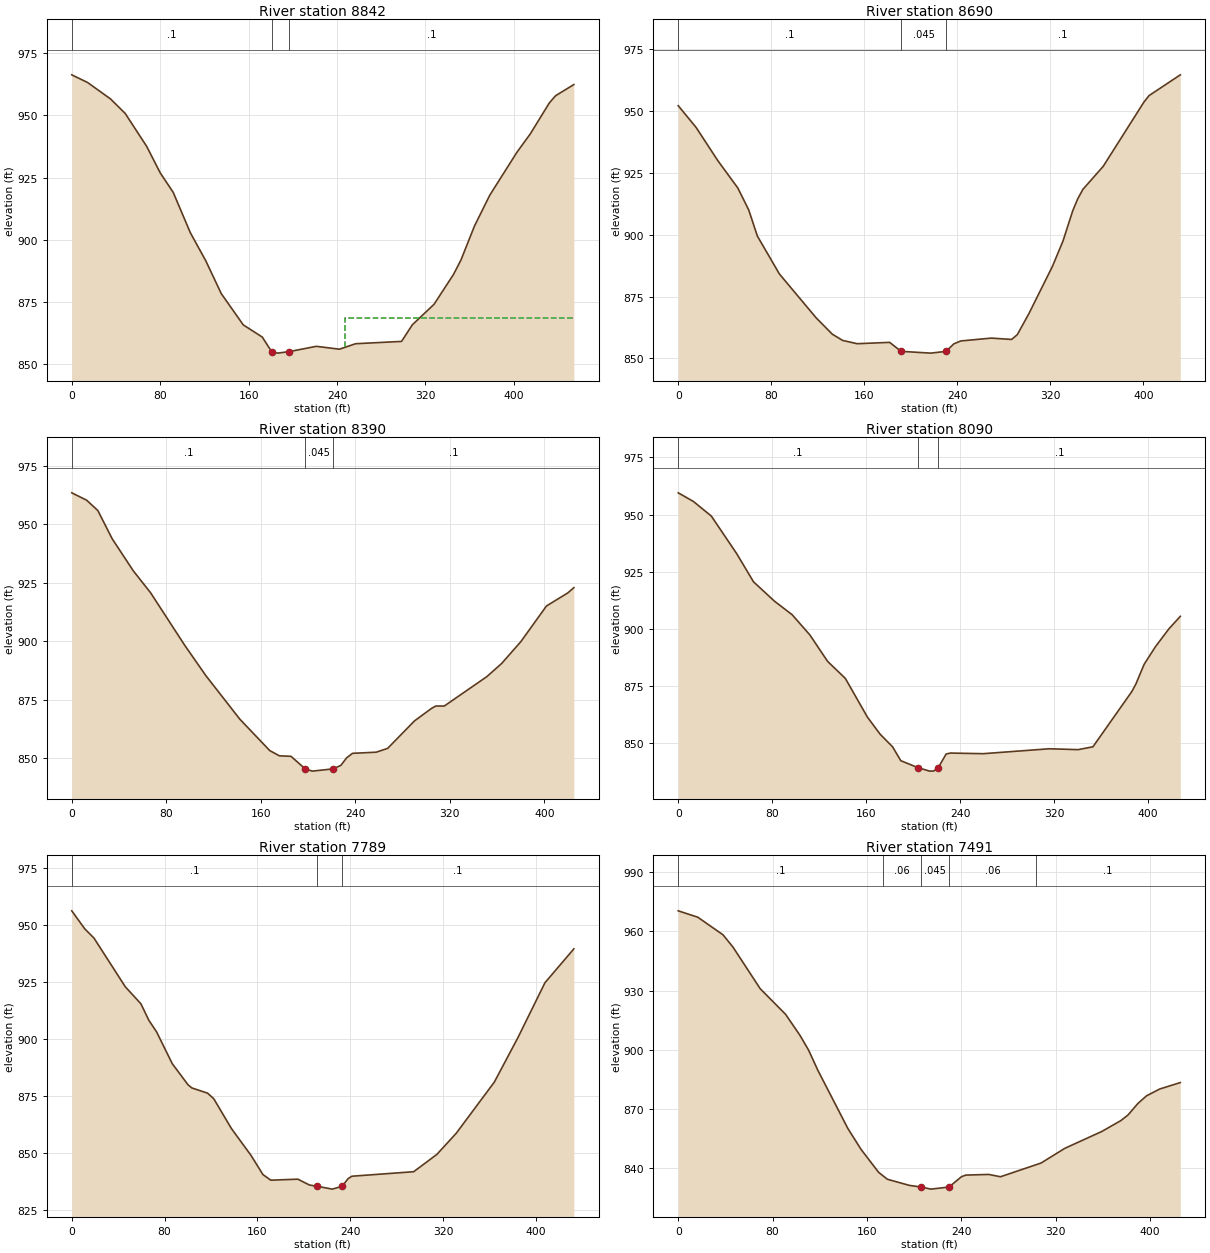
Type RM Length L Ch R = 1 ,8842    ,139.5,152.2,150.3
XS GIS Cut Line= 3
 1644146.2394693459138.3804211471644336.57599195458919.261302383
1644483.27438502458845.912105847
#Sta/Elev= 30
       0  966.22    14.3  963.14    35.1  956.54    48.4   950.7    67.8  937.49
    80.1  926.83    91.8  919.04   107.3  902.85   121.3  891.56   135.3  878.39
   155.2  865.86   172.4  860.97   180.8 855.152   186.4  854.53   196.7 855.134
   221.3  857.26   242.2  856.11   256.9  858.31   298.4  859.23   308.2  865.92
   327.8  874.12   345.3  886.03   352.2  891.94   364.4  905.55   378.3  917.97
   402.8  935.14     415  942.59   432.1  954.93   437.8  957.84   454.3  962.31
#Mann= 3, -1 ,  0
       0     0.1       0   180.8   0.045       0   196.7     0.1       0
#XS Ineff= 2 , 0
                          246.93          868.55
Permanent Ineff=
       F       F
Bank Sta=180.8,196.7
XS Rating Curve= 0 ,0
Exp/Cntr(USF)=0,0
Exp/Cntr=0.3,0.1

Type RM Length L Ch R = 1 ,8690    ,287.8,300,303
XS GIS Cut Line= 6
1644270.13389984459223.4315885011644315.54817909459143.425186843
1644357.44901392459078.4095688461644423.57125701459003.387737259
1644473.19320501458947.1503169241644531.08580576458881.540211916
#Sta/Elev= 30
       0  952.11    15.3  943.37    34.1  929.88    51.3  918.82    60.6  910.02
    68.1  899.39      87  884.12   118.7  866.34   132.5  859.79   141.4  857.26
   153.9  855.94   181.8  856.48  191.69852.8491   217.2  852.13   230.4  852.85
     237  855.87     243  857.05   269.3   858.2   286.7  857.66   291.6  859.58
   301.5  868.02   321.8  887.16   330.9  897.43   339.3  909.68   343.6   914.5
     348  918.28   365.5  927.61   400.5  953.56   404.9  956.18   431.8  964.58
#Mann= 3, -1 ,  0
       0     0.1       0  191.69   0.045       0   230.4     0.1       0
Bank Sta=191.69,230.4
XS Rating Curve= 0 ,0
Exp/Cntr(USF)=0,0
Exp/Cntr=0.3,0.1

Type RM Length L Ch R = 1 ,8390    ,298.4,300,299.7
XS GIS Cut Line= 6
1644357.90537784459365.7374062541644437.56237076459329.529473424
1644505.83979325459298.4941024181644596.87635659459257.113607749
1644665.15377909459226.078236759  1644744.810772459189.869975835
#Sta/Elev= 30
       0  963.52    12.6  960.37    22.1  955.93    34.2  943.89    52.2   930.1
    66.7  920.83    95.5  898.46   113.5   885.4   142.3  866.77   167.6  853.37
   175.7  851.14   185.6  850.91  197.62845.5506   203.6  844.59  221.23845.5487
   227.8  847.06   232.7  850.29   237.7   852.2   257.7  852.68   267.4  854.32
   290.1  866.05   304.5  871.39   308.1  872.41   315.3   872.4   351.4  884.99
   363.9   890.6   380.2  899.96   401.8  915.15   419.8  920.72     425  922.98
#Mann= 3, -1 ,  0
       0     0.1       0  197.62   0.045       0  221.23     0.1       0
Bank Sta=197.62,221.23
XS Rating Curve= 0 ,0
Exp/Cntr(USF)=0,0
Exp/Cntr=0.3,0.1

Type RM Length L Ch R = 1 ,8090    ,298.6,300.2,303.7
XS GIS Cut Line= 6
1644499.26008201459637.9255101681644575.70120209459592.354079008
1644641.73519076459554.8052695841644735.14051576459519.091430262
1644805.19450951 459492.306706921644886.92433292459461.057753667
#Sta/Elev= 30
       0  959.53      13  955.73    28.2  949.35    49.8  932.91    64.1  920.61
    81.8   912.2      97  906.21   112.1  897.36   127.2  885.79   142.3  878.34
   161.1  861.41   171.9  853.95   182.5  848.43   189.5  842.36  203.98 839.338
   214.1  837.79   217.6  837.85   221.4 839.335   228.1  845.26   231.6  845.69
   259.7  845.42   315.9  847.57   340.5  847.19   353.1  848.43   386.2  872.59
   389.7  875.92   396.7  884.52   406.4  892.27   417.8  900.04   427.5  905.51
#Mann= 3, -1 ,  0
       0     0.1       0  203.98   0.045       0   221.4     0.1       0
Bank Sta=203.98,221.4
XS Rating Curve= 0 ,0
Exp/Cntr(USF)=0,0
Exp/Cntr=0.3,0.1

Type RM Length L Ch R = 1 ,7789    ,293,298.5,307.2
XS GIS Cut Line= 6
1644623.06921759459844.7626949251644713.96995443459823.121005923
1644787.91468842459803.0659279231644886.49126293459786.250016674
1644960.47110184459773.9199888411645046.78031242459759.534847006
#Sta/Elev= 30
       0  956.35    11.2  948.44    19.1  944.42    46.1  923.05    59.6  915.55
    66.4  908.35    73.1  903.23    86.6  889.29   100.1  880.08   103.5  878.65
     117  876.37   122.3  873.95   137.5  860.89   154.5  849.02   164.7  840.66
   171.5  838.18   194.8  838.63   204.8  836.06  211.45835.5132   224.5  834.26
  232.92835.5126   238.1  838.87   241.4  839.92   294.6   841.9   314.6   849.5
   331.2  858.72   364.1  881.23   384.4  900.71   407.7   924.8   432.6  939.66
#Mann= 3, -1 ,  0
       0     0.1       0  211.45   0.045       0  232.92     0.1       0
Bank Sta=211.45,232.92
XS Rating Curve= 0 ,0
Exp/Cntr(USF)=0,0
Exp/Cntr=0.3,0.1

Type RM Length L Ch R = 1 ,7491    ,199.4,199.6,201.3
XS GIS Cut Line= 6
1644577.87016101459977.0350681691644655.41396917460018.699683011
1644720.97354934460055.6146354231644809.88839775460101.451486006
1644877.42992935460134.0570638331644956.22865626 460172.09701401
#Sta/Elev= 30
       0  970.42    16.6  967.18      38  958.25    46.4  952.06    69.5  930.94
    91.1   917.9   103.4  907.13   110.6  899.73   118.4  889.57   143.8   860.1
   155.1  849.39     170  837.76   177.4  834.28   195.9   831.2  205.92830.3441
   214.3  829.28  229.64 830.346   240.2  835.58   243.9   836.4   263.3  836.73
   273.3  835.56   307.7  842.51   327.9  849.98   359.3  858.54   375.3  864.01
   381.4  866.85   389.8   872.7   397.1  876.57   408.4  880.07   425.8  883.32
#Mann= 5, -1 ,  0
       0     0.1       0  173.27    0.06       0  205.92   0.045       0
  229.64    0.06       0   303.3     0.1       0
Bank Sta=205.92,229.64
XS Rating Curve= 0 ,0
Exp/Cntr(USF)=0,0
Exp/Cntr=0.3,0.1

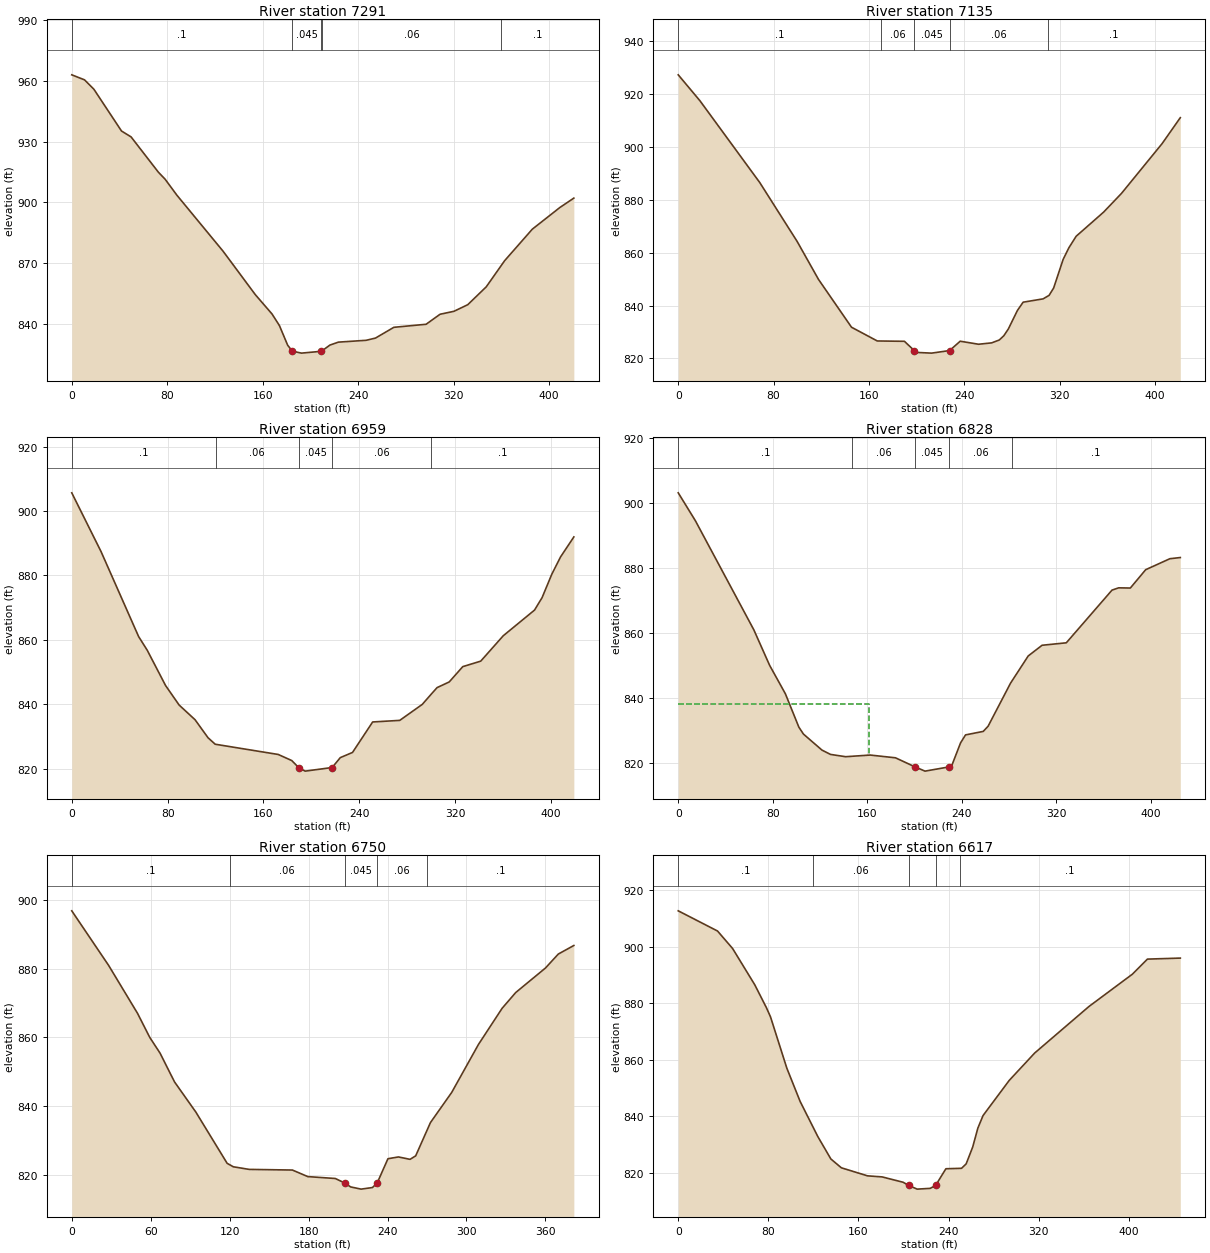
Type RM Length L Ch R = 1 ,7291    ,155.9,156.5,157.1
XS GIS Cut Line= 2
 1644484.9640171460138.3270696461644841.83293492460361.192013776
#Sta/Elev= 30
       0  962.95    10.7  960.47    18.5  955.87    41.7  935.21    49.7  932.32
    72.6  914.89    78.2  911.46    88.1  903.55   126.8  875.91   153.8  854.48
   167.8  844.95     174  839.22   180.9  829.55   184.8  826.59   192.5  825.63
   209.2  826.54   216.3   829.6   223.4  831.05   246.7  831.96   254.5  833.06
   269.9  838.37   296.9  839.87   308.6  844.81   320.2  846.26   331.8  849.52
   347.3  858.34   362.7  871.23   385.9  886.79   409.1  897.53   420.7  902.12
#Mann= 5, -1 ,  0
       0     0.1       0   184.8   0.045       0   209.2     0.1       0
     210    0.06       0     360     0.1       0
Bank Sta=184.8,209.2
XS Rating Curve= 0 ,0
Exp/Cntr(USF)=0,0
Exp/Cntr=0.3,0.1

Type RM Length L Ch R = 1 ,7135    ,176.3,176.1,175.9
XS GIS Cut Line= 2
1644425.05390098460284.4432080681644789.44094823460495.904767612
#Sta/Elev= 30
       0  927.32    18.2  917.52    68.4  886.57    99.8  864.27   117.7  849.92
   145.4  831.83     167  826.63   189.8   826.5  198.12 822.979   201.2  822.27
   212.6  822.03   227.7     823   236.6  826.54     252  825.39     263  825.91
   269.4     827   273.2   828.6     277  831.17   284.6  838.16   289.4   841.3
   306.2  842.56   311.2  843.89     315  846.66     323  857.51   327.8  861.89
   333.9  866.24   356.9  875.36   371.9  882.44     406  901.28   421.3  911.11
#Mann= 5, -1 ,  0
       0     0.1       0     170    0.06       0  198.12   0.045       0
   227.7    0.06       0     310     0.1       0
Bank Sta=198.12,227.7
XS Rating Curve= 0 ,0
Exp/Cntr(USF)=0,0
Exp/Cntr=0.3,0.1

Type RM Length L Ch R = 1 ,6959    ,129.9,130.5,130.6
XS GIS Cut Line= 2
1644346.89700759 460446.049134521644712.74745663460650.202718427
#Sta/Elev= 30
       0  905.65    24.5  887.36    55.8  861.03      63  856.78    78.3  845.83
    89.6  839.78   102.9  835.22   113.7  829.64   119.7  827.62   172.3  824.44
   183.6  822.55   189.6 820.282   194.8  819.27   217.3  820.39   224.1  823.46
   234.3  825.07   251.1  834.53   273.7  835.02   292.5  839.98     300  843.17
   304.9   845.2     315  846.95   326.3   851.7   341.3  853.41   360.1  861.29
   386.2  869.26   392.5  873.12   400.6  880.38   407.9  885.75     419  891.96
#Mann= 5, -1 ,  0
       0     0.1       0     120    0.06       0   189.6   0.045       0
   217.3    0.06       0     300     0.1       0
Bank Sta=189.6,217.3
XS Rating Curve= 0 ,0
Exp/Cntr(USF)=0,0
Exp/Cntr=0.3,0.1

Type RM Length L Ch R = 1 ,6828    ,76.3,77.9,78.7
XS GIS Cut Line= 6
1644274.92309851460548.6933473781644350.22380094460593.258546961
1644414.76730702460631.4572894551644500.82454961460682.389602301
1644565.36805568460720.588672874 1644640.6687581  460765.1532163
#Sta/Elev= 30
       0  903.22    14.5  894.62      64  860.94    77.3  850.03    90.7  841.21
   102.1  830.92     106  828.77   121.7  823.82   128.9   822.5   141.7  821.79
   162.5   822.3   183.9  821.45   200.2  818.69   208.9  817.34  229.54818.6608
   231.9  819.39     239  826.07   243.2  828.52   258.2   829.6   262.3   831.2
   281.3  844.49   296.3   852.9     308  856.18   328.5  856.94   367.2   873.2
   372.8   873.9   382.7  873.84   395.7   879.5   416.2  882.89     425  883.25
#Mann= 5, -1 ,  0
       0     0.1       0   147.5    0.06       0   200.2   0.045       0
  229.54    0.06       0   282.5     0.1       0
#XS Ineff= 2 , 0
          161.39  838.07
Permanent Ineff=
       F       F
Bank Sta=200.2,229.54
XS Rating Curve= 0 ,0
Exp/Cntr(USF)=0,0
Exp/Cntr=0.3,0.1

Type RM Length L Ch R = 1 ,6750    ,129.5,132.9,133.7
XS GIS Cut Line= 2
1644240.57494122460594.6301887861644549.51532041460818.657130419
#Sta/Elev= 30
       0   896.8      28  880.94      50  866.98    59.3  859.98    67.1  855.42
    78.1  847.05    94.3  838.28   118.1  823.37   122.8  822.37   134.8  821.61
   167.7  821.42   179.4  819.51   200.3  818.96  207.42817.6609     212  816.51
   219.9  815.87   228.5  816.33   232.1  817.62   240.3  824.71   248.3  825.23
   257.1  824.53   261.4  825.55   272.6  835.21   288.8  844.01   309.1  857.94
   327.1  868.46   337.4  873.03     360  880.16   369.8  884.23   381.6  886.72
#Mann= 5, -1 ,  0
       0     0.1       0     120    0.06       0  207.42   0.045       0
   232.1    0.06       0     270     0.1       0
Bank Sta=207.42,232.1
XS Rating Curve= 0 ,0
Exp/Cntr(USF)=0,0
Exp/Cntr=0.3,0.1

Type RM Length L Ch R = 1 ,6617    ,130.1,122.2,116.1
XS GIS Cut Line= 4
1644147.49306901460690.0726840941644247.26957107460736.501999228
1644367.73699135460858.0741708131644513.31254734460934.665698841
#Sta/Elev= 30
       0  912.78    34.9  905.62    48.3  899.41      68  886.53    78.3  878.44
    81.9  875.22    96.4  857.03   108.2  845.24   123.9   832.8   135.5  824.84
   144.8  821.72     168  818.87     181  818.49   199.6   816.6  204.64 815.461
   212.1  814.16   223.7  814.43  228.46815.4531   237.6  821.38   251.5  821.54
   255.6  823.11   261.4  829.08     266   835.8   270.6  840.24   293.8  852.67
   316.4  862.38   364.6  878.88   403.2  890.34   416.5  895.67   445.7  896.03
#Mann= 5, -1 ,  0
       0     0.1       0  120.05    0.06       0  204.64   0.045       0
  228.46    0.06       0  250.05     0.1       0
Bank Sta=204.64,228.46
XS Rating Curve= 0 ,0
Exp/Cntr(USF)=0,0
Exp/Cntr=0.3,0.1

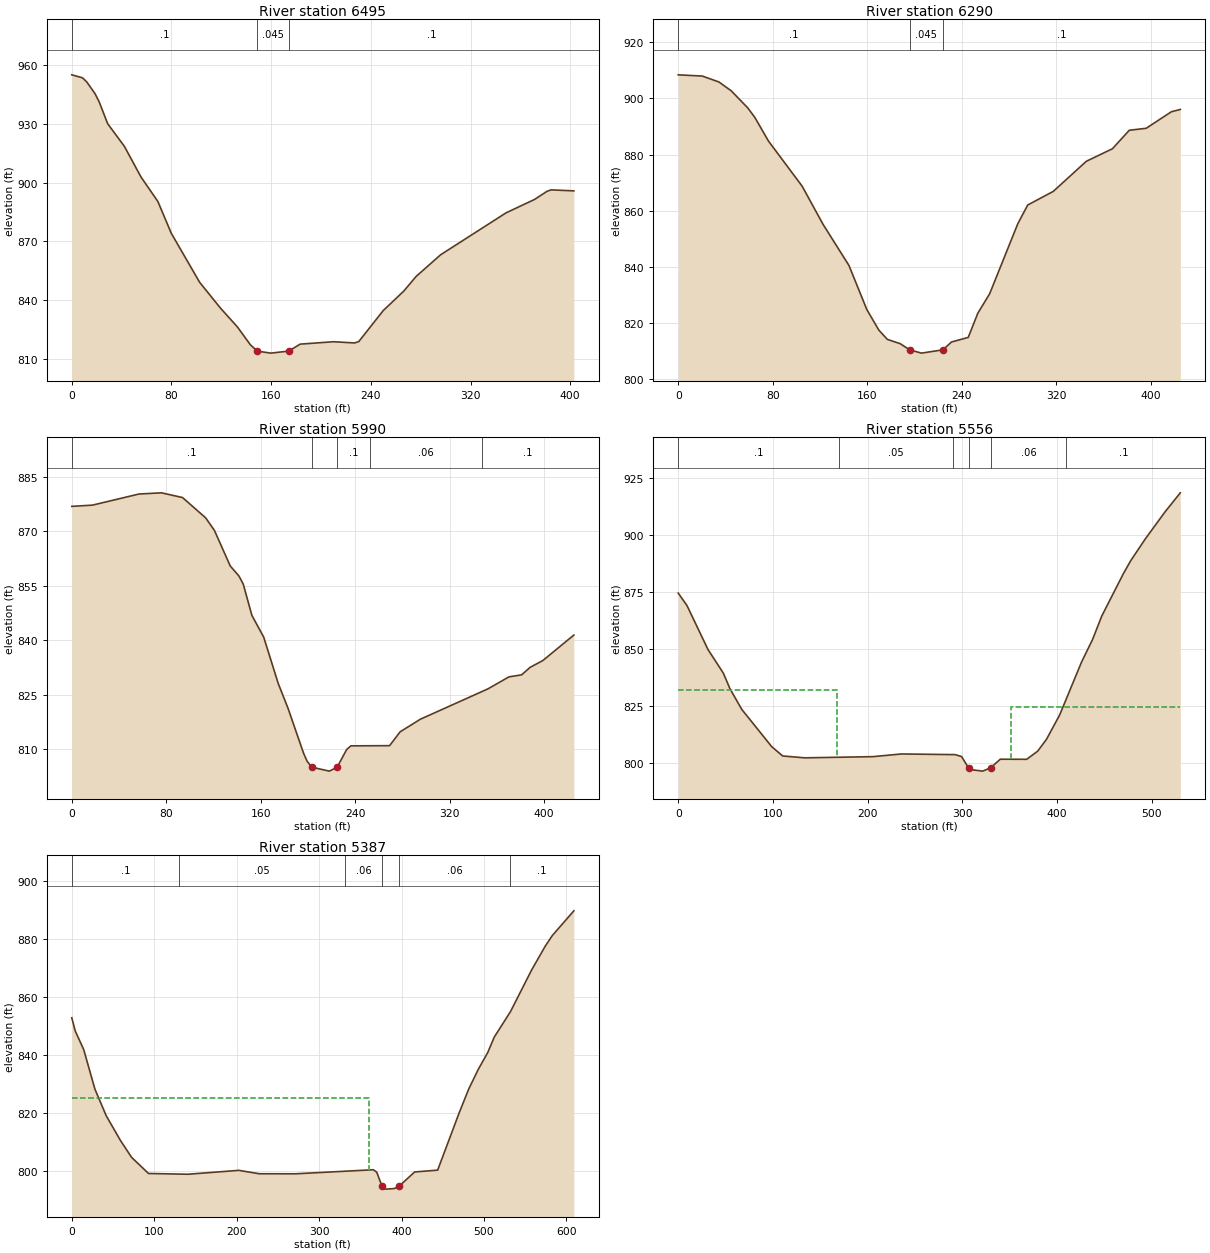
Type RM Length L Ch R = 1 ,6495    ,214.6,205.7,198.8
XS GIS Cut Line= 3
1644105.07477491460881.8905413641644331.81171987460931.573935678
1644502.54192943 460936.99394233
#Sta/Elev= 30
       0  955.14     8.6  953.62      12  951.52    18.7  945.47      22  941.32
    28.8  930.16    42.2   918.6    55.6  902.86    69.1  890.38    79.9  874.08
   102.6  849.08   119.4  835.81   132.9  826.26   143.3  817.14   148.9813.8633
   159.8  812.85  174.12813.8978   183.3  817.45   210.1  818.68   226.9  818.05
   230.3  818.75     250  834.65   266.4  844.55   276.3  852.04     296  863.14
   348.5  884.57   371.5  891.47   381.3  895.55   384.6  896.32   402.9  895.81
#Mann= 3, -1 ,  0
       0     0.1       0   148.9   0.045       0  174.12     0.1       0
Bank Sta=148.9,174.12
XS Rating Curve= 0 ,0
Exp/Cntr(USF)=0,0
Exp/Cntr=0.3,0.1

Type RM Length L Ch R = 1 ,6290    ,298.5,300,299.2
XS GIS Cut Line= 6
1644146.89595734461184.0726803391644228.99028134461153.284028009
1644297.21980368461122.1430141781644388.15072417461080.531220749
1644456.63385493461049.9443396781644537.05987518461015.416849673
#Sta/Elev= 30
       0  908.35    20.4  907.91    34.4  905.82    44.9  902.66    58.9  896.58
    64.9  893.18    76.4  884.81     105   868.7   122.5  855.27   144.6  840.52
   159.7  824.87   169.9  817.53   177.1  814.24   187.9  812.73  196.04810.5224
     206  809.35  224.17810.5237   231.4  813.31   245.6  814.94   253.7  823.54
   263.7  830.43   287.6   855.4     296  862.05   317.6  866.88   345.6  877.59
   367.7  882.05     382  888.63   396.3  889.33   417.7  895.23   425.2  896.03
#Mann= 3, -1 ,  0
       0     0.1       0  196.04   0.045       0  224.17     0.1       0
Bank Sta=196.04,224.17
XS Rating Curve= 0 ,0
Exp/Cntr(USF)=0,0
Exp/Cntr=0.3,0.1

Type RM Length L Ch R = 1 ,5990    ,414.8,433.7,443.3
XS GIS Cut Line= 6
1644232.21107543 461481.690851511644310.93106234461443.488828167
1644378.40566492461410.7441430091644468.37136425461367.085109591
1644536.25344634461335.1799896661644616.68865292461300.410374179
#Sta/Elev= 30
       0  876.86    17.5   877.2    56.9  880.26    75.9  880.59    93.8  879.29
   113.4  873.69   120.8  870.23   134.2  860.44   141.5  857.71   145.2  855.46
   152.5  846.86   162.5  840.87   174.8  828.11   183.2  821.18   196.2  808.94
   199.3  806.65  203.43805.0335   218.1  803.96  224.71805.0338   232.7  809.89
   236.3  810.92   269.1  810.97     278  814.78   295.2  818.26   352.3   826.6
   370.2  829.92   380.9  830.47     388  832.52   398.8   834.4   425.1  841.42
#Mann= 5, -1 ,  0
       0     0.1       0  203.43   0.045       0  224.71     0.1       0
   252.5    0.06       0  347.51     0.1       0
Bank Sta=203.43,224.71
XS Rating Curve= 0 ,0
Exp/Cntr(USF)=0,0
Exp/Cntr=0.3,0.1

Type RM Length L Ch R = 1 ,5556    ,172.4,169.2,167
XS GIS Cut Line= 2
1644200.51964649461493.3871643241644560.17878769461883.189322876
#Sta/Elev= 30
       0   874.6     9.2  869.18    31.5   849.8    47.7  839.45    54.6  832.68
    67.2  823.52    98.7  807.24   110.3  803.13   133.6   802.3   205.6  802.82
   235.7     804   292.6  803.71   299.3  802.87  306.72797.8866     310  797.08
   321.6  796.47  330.05 797.925   340.2   801.7   368.1  801.66   379.7  805.22
     389  810.42   402.9  821.08   426.1  844.38   437.7  854.24   447.4  864.52
   470.2   883.1   477.9  888.76   493.4  898.38   514.3  910.29   530.4  918.62
#Mann= 6, -1 ,  0
       0     0.1       0     170    0.05       0     290    0.06       0
  306.72   0.045       0  330.05    0.06       0     410     0.1       0
#XS Ineff= 2 , 0
          167.21  831.88  352.06          824.42
Permanent Ineff=
       F       F
Bank Sta=306.72,330.05
XS Rating Curve= 0 ,0
Exp/Cntr(USF)=0,0
Exp/Cntr=0.3,0.1

Type RM Length L Ch R = 1 ,5387    ,278.2,302.3,316.8
XS GIS Cut Line= 6
1644117.13061803461519.0858122331644194.06482625 461779.37103042
1644257.81535493461818.8784973321644342.81649725461871.554901168
1644406.56735401461911.0623680951644478.41727592461961.229918674
#Sta/Elev= 30
       0  852.88     4.2  848.33    14.5  841.89    28.1  828.24    41.8  819.05
    58.9  810.61    72.6  804.68    93.1  799.13     141  798.87   202.6  800.21
   227.4  799.04   271.4  799.02   365.7  800.42   369.9  799.58   376.3794.7732
   381.2  793.73   391.3  793.93   397.3794.8052   415.9  799.66   443.8  800.28
     470  820.13   481.5  828.28   493.1  835.08   504.7  840.96   512.4  846.18
   532.1  854.98   557.7  869.33   574.2  877.55     583   881.3     609   889.8
#Mann= 6, -1 ,  0
       0     0.1       0     130    0.05       0  331.42    0.06       0
   376.3   0.045       0   397.3    0.06       0  531.42     0.1       0
#XS Ineff= 2 , 0
          360.49  825.23
Permanent Ineff=
       F       F
Bank Sta=376.3,397.3
XS Rating Curve= 0 ,0
Exp/Cntr(USF)=0,0
Exp/Cntr=0.3,0.1