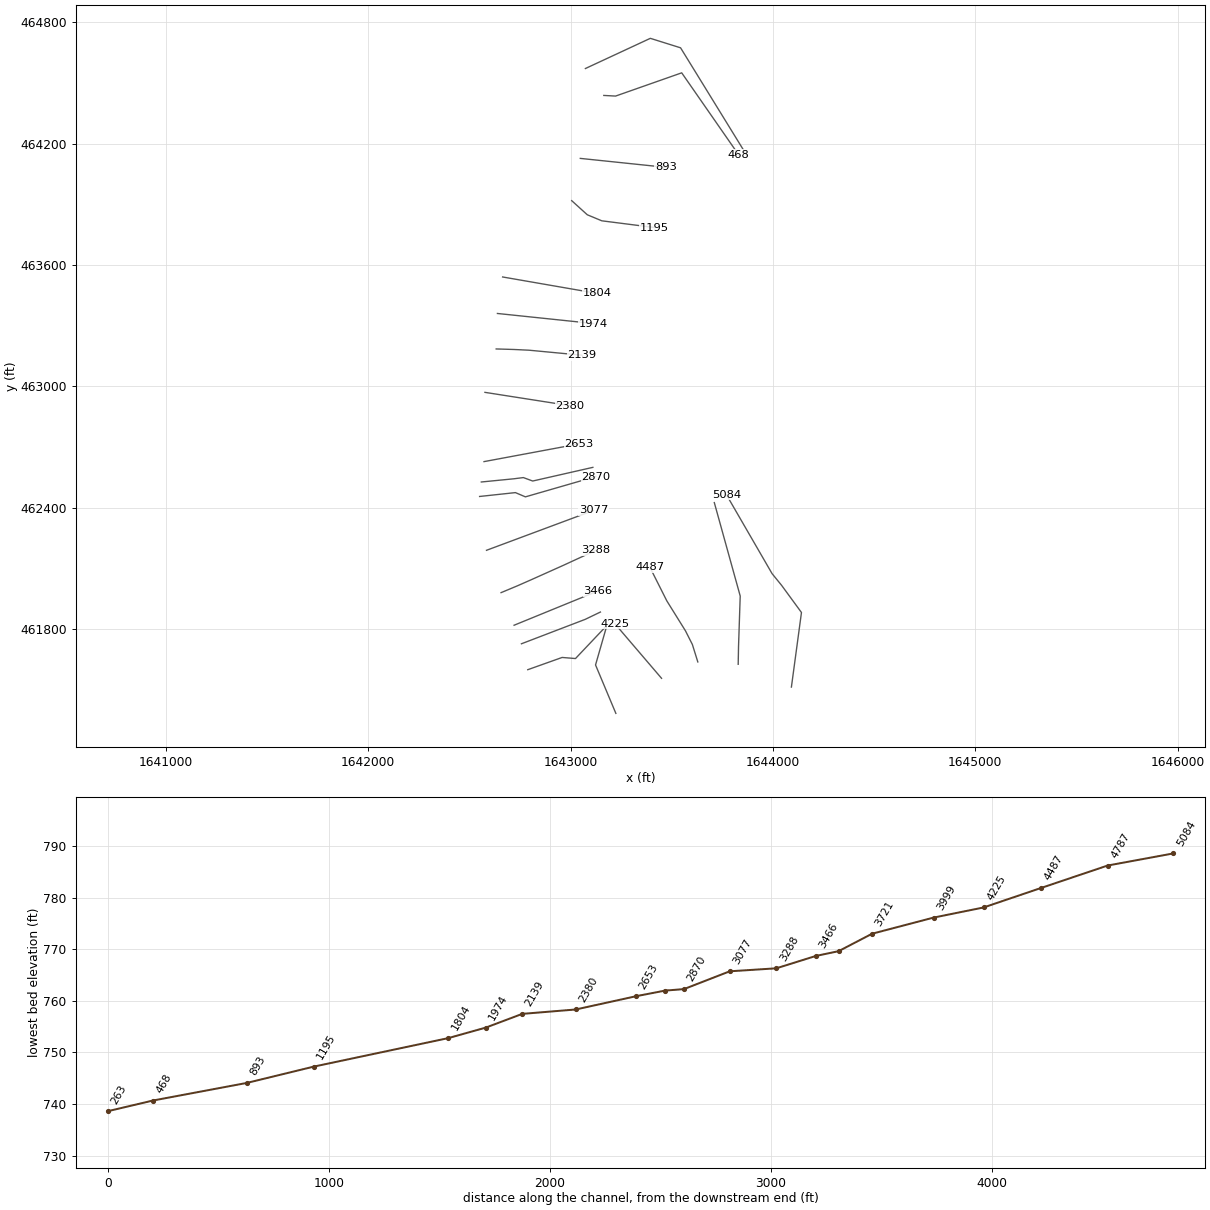
HEC-RAS study VallyRn.prj: VallyRn

--- VallyRn.g01 (geometry) --- (continued)

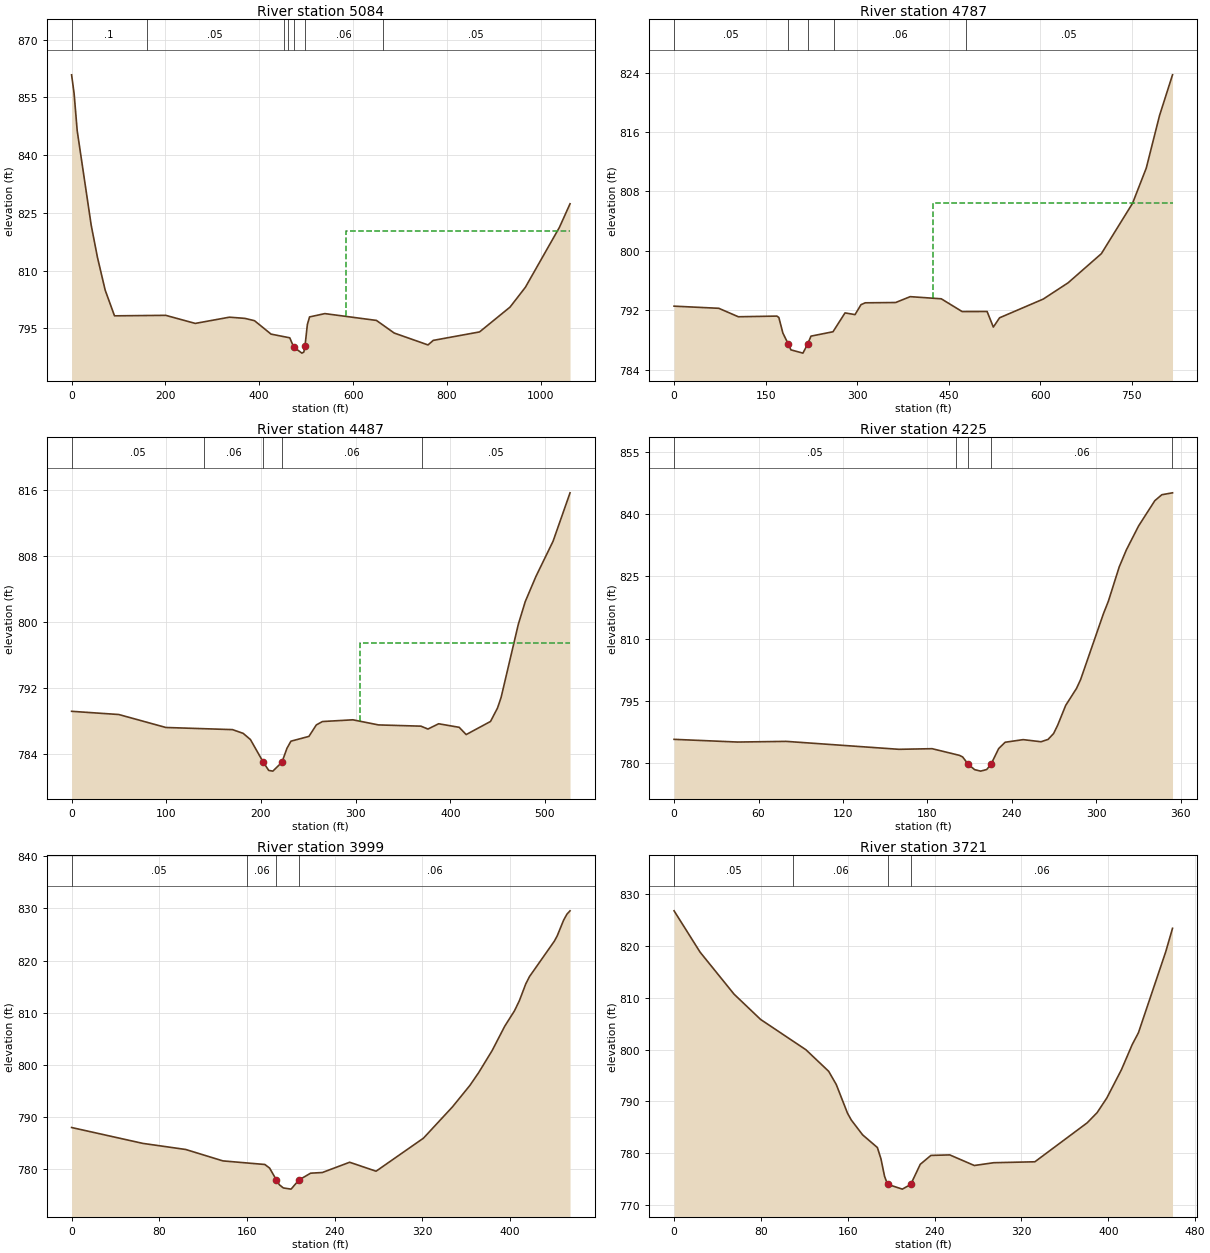
Type RM Length L Ch R = 1 ,5084    ,312.1,297.5,292.5
XS GIS Cut Line= 5
1644091.28932935 461514.455265181644141.02749303461882.978310684
1644042.99852733462016.9535605011643995.70367442462075.161777422
1643770.54797915462464.330428542
#Sta/Elev= 30
       0  860.88     5.4  855.99      12  846.32    41.8  821.81    55.1  813.47
    71.6  804.93    91.5  798.25   200.7  798.38   263.6  796.28   336.5   797.9
   369.6  797.59     390  796.98   425.2   793.5   465.1  792.54473.5551 790.108
   490.9  788.56   495.1  788.84497.4506790.3046   502.6  796.02   507.3  797.97
   539.9  798.83   649.8  797.06   687.7  793.78   759.7  790.69   770.9  791.87
   869.6  794.07   934.6  800.52   967.3  805.67  1039.9  821.25  1062.5  827.37
#Mann= 7, -1 ,  0
       0     0.1       0     160    0.05       0  451.86    0.06       0
  461.86    0.05       0473.5551   0.045       0497.4506    0.06       0
  662.87    0.05       0
#XS Ineff= 2 , 0
                          584.74          820.32
Permanent Ineff=
       F       F
Bank Sta=473.5551,497.4506
XS Rating Curve= 0 ,0
Exp/Cntr(USF)=0,0
Exp/Cntr=0.3,0.1

Type RM Length L Ch R = 1 ,4787    ,291.8,300,303.6
XS GIS Cut Line= 6
1643828.31916668461627.0117550941643829.97533134461714.505018428
1643832.47335784461789.463858008 1643835.8027475461889.408211917
1643838.30143018461964.3663953391643710.26475922462426.098362239
#Sta/Elev= 30
       0  792.54    73.3  792.25   105.3  791.11   168.5   791.2   171.7  791.01
   178.3  788.91  187.33787.4099   191.4  786.65   211.1  786.21  218.82787.4091
   224.3   788.5   260.4  789.09   280.1  791.63   296.5   791.4   306.3  792.74
   313.3  792.99   363.1  793.03   386.9  793.82   437.8  793.53     472  791.81
   512.9  791.82   523.1  789.72   533.3  790.97   604.8  793.49   645.7  795.69
   700.1  799.61   751.2   806.4   773.7  811.15   795.4  818.22   816.7  823.71
#Mann= 5, -1 ,  0
       0    0.05       0  187.33   0.045       0  218.82    0.05       0
  262.51    0.06       0  477.51    0.05       0
#XS Ineff= 2 , 0
                          424.53          806.46
Permanent Ineff=
       F       F
Bank Sta=187.33,218.82
XS Rating Curve= 0 ,0
Exp/Cntr(USF)=0,0
Exp/Cntr=0.3,0.1

Type RM Length L Ch R = 1 ,4487    ,260.1,261.6,262.1
XS GIS Cut Line= 6
1643628.76608808461638.6078605061643601.88097125461724.808803588
1643567.93484493461792.020283341 1643515.1048981461876.925625339
  1643475.482602461940.6052879991643391.86075974 462106.68575083
#Sta/Elev= 30
       0  789.13    49.9  788.74    99.6  787.17     170  786.91   181.2  786.46
   188.9  785.71   202.4782.9781   208.2  781.97   212.6  781.88   222.2  782.96
   227.5  784.65   231.7  785.51   250.7  786.09   258.5  787.48     265  787.89
   297.1   788.1   324.2  787.48     369  787.33   376.4  786.98   387.7  787.62
   409.4  787.19   416.8  786.31   442.5   787.9   449.9  789.53   453.7  790.82
   471.9  799.69   479.2  802.43   490.4  805.46   508.6  809.75   526.5  815.61
#Mann= 5, -1 ,  0
       0    0.05       0   140.3    0.06       0   202.4   0.045       0
   222.2    0.06       0  370.59    0.05       0
#XS Ineff= 2 , 0
                          304.58          797.46
Permanent Ineff=
       F       F
Bank Sta=202.4,222.2
XS Rating Curve= 0 ,0
Exp/Cntr(USF)=0,0
Exp/Cntr=0.3,0.1

Type RM Length L Ch R = 1 ,4225    ,228.7,226,222.2
XS GIS Cut Line= 2
1643449.55534201461557.6879500991643219.47605961461826.791280392
#Sta/Elev= 30
       0  785.73    45.1  785.08    79.7  785.24   159.7  783.33   183.3  783.48
   202.7  781.88     205  781.49  209.01779.7168   213.5  778.44   217.8  778.08
   222.1  778.47  225.13  779.71   230.6  783.51   235.2  785.03     248  785.66
   260.7  785.15   265.7  785.72   269.6  787.12   272.5  789.12   278.2   793.9
   285.9  797.99   288.8  800.11     305  815.95   308.5  818.95   316.2   827.2
   321.3  831.32     330  837.09   341.5  843.16   346.5   844.6   354.1  845.06
#Mann= 5, -1 ,  0
       0    0.05       0     200    0.06       0  209.01   0.045       0
  225.13    0.06       0  354.05     0.1       0
Bank Sta=209.01,225.13
XS Rating Curve= 0 ,0
Exp/Cntr(USF)=0,0
Exp/Cntr=0.3,0.1

Type RM Length L Ch R = 1 ,3999    ,300,278.4,258.1
XS GIS Cut Line= 3
1643223.71264021461384.421009526 1643123.3234113461623.673645792
1643177.13640078 461811.27106438
#Sta/Elev= 30
       0  787.95      65   784.9   104.1  783.73     138  781.54   176.3  780.85
   180.6  780.16   186.8 777.879   189.5  776.96   193.1  776.35   200.2  776.12
   207.3  777.87     218  779.18   228.7  779.31   253.6  781.28   277.7  779.56
   320.9   785.9   347.4  791.92   363.3  796.04   371.3   798.5   383.5   802.7
   395.1  807.42     404  810.38   408.4   812.3   414.2  815.51   417.6  816.92
   440.2   823.7   442.9  824.74   448.7  827.74   451.8  828.92   454.6  829.55
#Mann= 4, -1 ,  0
       0    0.05       0     160    0.06       0   186.8   0.045       0
   207.3    0.06       0
Bank Sta=186.8,207.3
XS Rating Curve= 0 ,0
Exp/Cntr(USF)=0,0
Exp/Cntr=0.3,0.1

Type RM Length L Ch R = 1 ,3721    ,146,151.4,155
XS GIS Cut Line= 4
1642788.41474946461600.2894419551642958.24162457461660.812849573
1643024.18503884461655.3928429211643170.52521845461809.863032515
#Sta/Elev= 30
       0  826.83      24  818.83    55.3   810.7    79.7  805.82   121.5  799.95
   142.4  795.79   149.4  793.24   159.8  787.67   163.3  786.35   173.7  783.49
   187.3  781.04   190.6  778.85   193.9  775.48  196.64 773.926   210.3  772.99
  218.02773.8973   226.8  777.79   236.6  779.51     254  779.61   276.6  777.56
   294.5   778.1   332.4  778.28   380.6  785.82   389.7  787.78   398.7  790.63
   412.2  796.12   422.1  800.97   427.8  803.25   452.9  818.88   459.2  823.45
#Mann= 4, -1 ,  0
       0    0.05       0     110    0.06       0  196.64   0.045       0
  218.02    0.06       0
Bank Sta=196.64,218.02
XS Rating Curve= 0 ,0
Exp/Cntr(USF)=0,0
Exp/Cntr=0.3,0.1

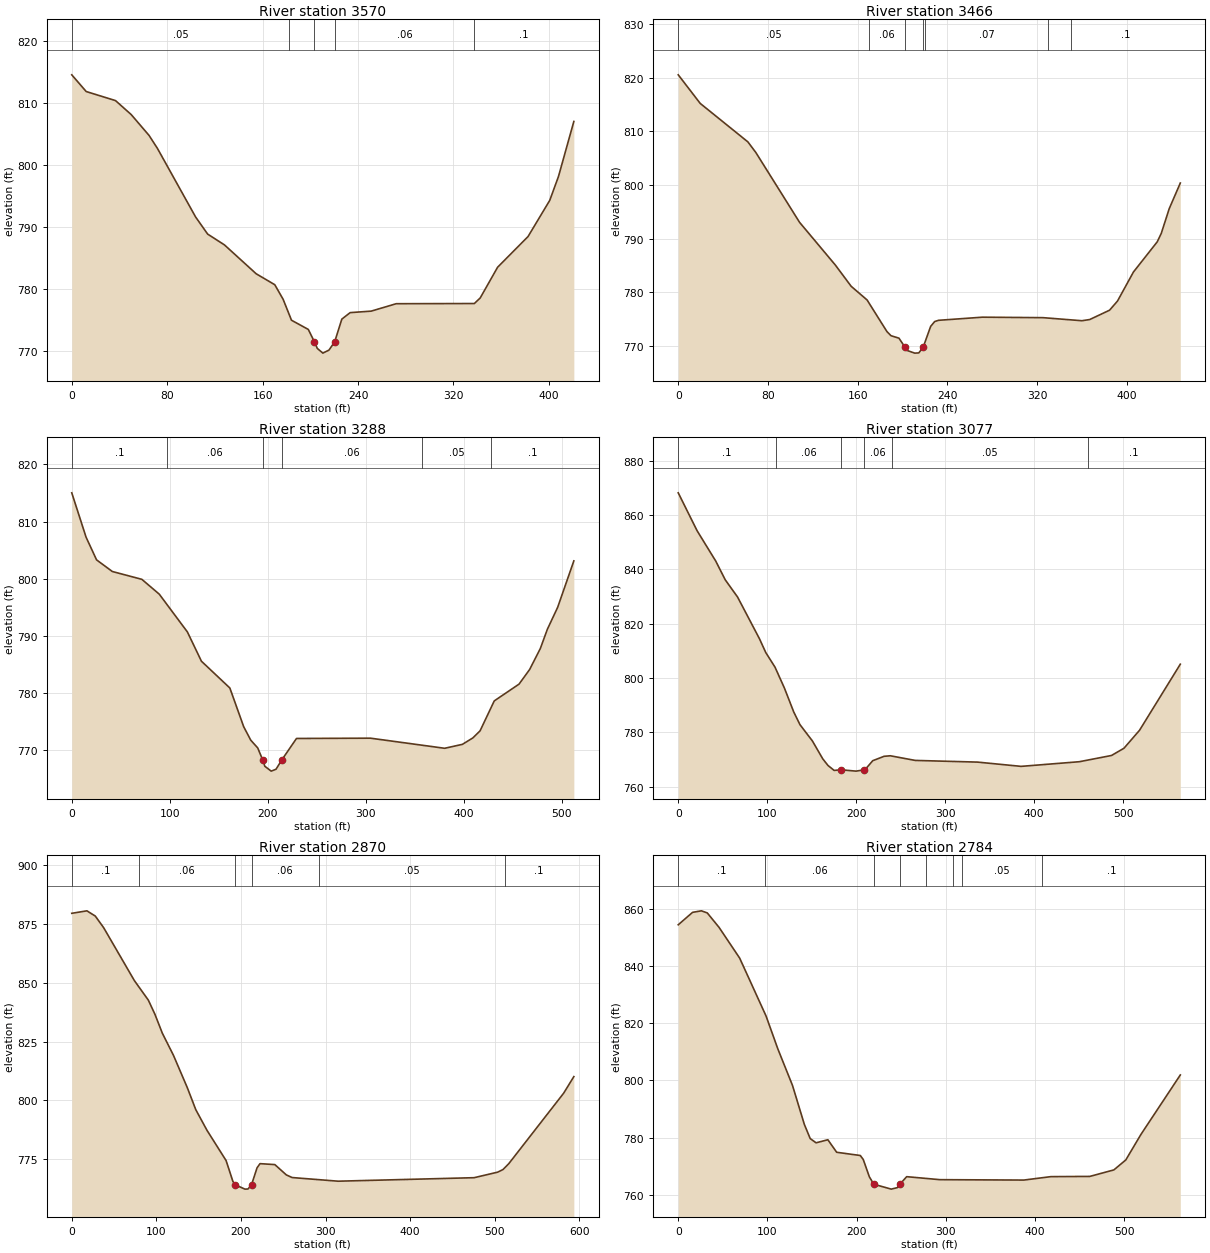
Type RM Length L Ch R = 1 ,3570    ,103.2,103.4,103.6
XS GIS Cut Line= 6
1642757.08746389461728.3683686551642838.79989888461759.662269324
1642908.83945696 461786.485050321643002.22509697461822.250070646
1643072.26432696461849.0731797361643147.40137021461885.255534191
#Sta/Elev= 30
       0  814.61    12.1  811.91    36.7  810.44    49.9  808.17    64.8  804.81
    71.8  802.72   103.8  791.63   113.9  788.86     128  787.11   154.6  782.44
   170.2  780.67   177.2  778.31   184.2  774.93   198.3  773.44  203.45771.4265
   205.8  770.38   210.5  769.61   215.6   770.1  220.38771.4237   226.4  775.11
   233.4  776.16     251   776.4     272   777.6   337.5  777.63   342.4  778.53
     357   783.5   382.5  788.46   400.7  794.31     408  798.16   420.9  807.07
#Mann= 5, -1 ,  0
       0    0.05       0   182.5    0.06       0  203.45   0.045       0
  220.38    0.06       0   337.5     0.1       0
Bank Sta=203.45,220.38
XS Rating Curve= 0 ,0
Exp/Cntr(USF)=0,0
Exp/Cntr=0.3,0.1

Type RM Length L Ch R = 1 ,3466    ,177.8,178.2,178.4
XS GIS Cut Line= 2
1642720.71891318461820.0047205211643135.14303612461989.354112953
#Sta/Elev= 30
       0  820.56    19.6  815.23    62.1  808.06    69.2  806.08   108.2  793.06
   140.1   785.1   154.2  781.14   168.4  778.59   186.1   772.7   189.7  771.93
   196.8  771.47  202.14769.8109   203.9  769.19   210.9  768.68   214.5  768.72
  218.41769.7791   225.1  773.67   228.7  774.57   232.2   774.8   271.2  775.38
   325.3  775.29     360  774.72   366.9  774.94   384.6  776.68   391.7  778.39
   405.9   783.8   427.1  789.42   430.7  790.99   437.8   795.6   447.7  800.39
#Mann= 7, -1 ,  0
       0    0.05       0     170    0.06       0  202.14   0.045       0
  218.41    0.06       0     220    0.07       0     330    0.06       0
     350     0.1       0
Bank Sta=202.14,218.41
XS Rating Curve= 0 ,0
Exp/Cntr(USF)=0,0
Exp/Cntr=0.3,0.1

Type RM Length L Ch R = 1 ,3288    ,211.7,210.8,210.3
XS GIS Cut Line= 6
1642656.42715351461981.0658370111642737.17961667462014.832829833
1642805.82941376462045.0397904221642897.08054359462085.945548505
1642965.51839884462116.6249490831643124.22415221462189.815574323
#Sta/Elev= 30
       0  815.03    14.6  807.26    25.3  803.29    41.4  801.25    71.5  799.88
    89.3  797.28     118  790.66   132.3  785.54   161.3  780.85   175.4  774.08
   182.6  771.72   189.8  770.34  194.68768.3008     197  767.14   203.5  766.29
   208.4  766.62  214.48768.2965   229.3  772.01   304.8  772.06   380.5  770.29
   398.6  770.98   409.2   772.1   416.6  773.34   431.1  778.59   456.4  781.53
   467.2  784.09   478.1  787.76   485.3  791.14   495.8  794.98   512.3  803.11
#Mann= 6, -1 ,  0
       0     0.1       0   97.53    0.06       0  194.68   0.045       0
  214.48    0.06       0  357.53    0.05       0  427.53     0.1       0
Bank Sta=194.68,214.48
XS Rating Curve= 0 ,0
Exp/Cntr(USF)=0,0
Exp/Cntr=0.3,0.1

Type RM Length L Ch R = 1 ,3077    ,218,207.2,201.6
XS GIS Cut Line= 2
1642584.41330464462190.3704649461643113.11384686462387.256343952
#Sta/Elev= 30
       0  868.12    21.2  854.17    42.2  842.98    52.8  836.12    66.7  829.76
    91.3  814.41    98.3  809.39   108.8  803.94   119.3  796.29   129.8  787.48
   136.8  782.81   150.8   776.8   162.4  770.23   168.3  767.79   175.2  765.97
   182.9   766.2   199.8  765.71   208.7766.1727   210.3   766.4   218.6  769.55
   231.3  771.16   238.3  771.36   266.3  769.65   336.3  769.03   385.3  767.46
   450.7  769.17   486.9  771.47   500.9  774.13   518.4  780.75   564.2  805.06
#Mann= 6, -1 ,  0
       0     0.1       0     110    0.06       0   182.9   0.045       0
   208.7    0.06       0     240    0.05       0     460     0.1       0
Bank Sta=182.9,208.7
XS Rating Curve= 0 ,0
Exp/Cntr(USF)=0,0
Exp/Cntr=0.3,0.1

Type RM Length L Ch R = 1 ,2870    ,84.5,85.5,86.9
XS GIS Cut Line= 4
1642550.40729151462456.4134883331642727.33670643462475.467425324
1642776.72140027462454.469209048 1643124.3585364462554.794020147
#Sta/Elev= 30
       0   879.5    17.9  880.56    27.8  878.33    37.7  873.39      74   850.9
    90.5   842.6    98.2  836.66     107  828.58   120.2  819.13   136.7  805.27
   146.6  796.02   159.8  787.27   182.4   774.4   190.4  765.59  192.93764.1317
   204.7  762.26   208.3  762.31  212.48764.1352     219  771.33   222.5  773.09
     240  772.69   253.6   768.3   260.5  767.18   314.8  765.63   475.6  767.12
   503.4  769.48   509.7  770.59   516.6  773.12   581.4  803.06   593.4  810.09
#Mann= 6, -1 ,  0
       0     0.1       0      80    0.06       0  192.93   0.045       0
  212.48    0.06       0  291.62    0.05       0  511.62     0.1       0
Bank Sta=192.93,212.48
XS Rating Curve= 0 ,0
Exp/Cntr(USF)=0,0
Exp/Cntr=0.3,0.1

Type RM Length L Ch R = 1 ,2784    ,122.7,131.3,137.5
XS GIS Cut Line= 6
1642558.73664546462527.9381026371642645.78568396462536.511904393
1642720.41906488462543.8626114771642766.61114799462549.738894006
 1642812.7885552462532.7069345031643110.03625068462600.221224564
#Sta/Elev= 30
       0   854.5    16.1  858.86      26  859.39    32.6  858.65    45.8  853.59
    68.9  842.84    98.5  822.57   111.7  811.07   128.2  798.23   141.4  784.67
     148  779.67   154.6  778.18   167.8  779.26   177.7  774.87   204.2  773.74
   207.5  772.35   214.4  766.24  219.37763.6825   238.9  761.97   245.9  762.51
   248.6763.6823   256.2  766.33   293.4  765.28   387.6  765.14   417.9  766.34
   461.6  766.42   488.6   768.7     502   772.2   518.8  781.05   563.1  801.93
#Mann= 8, -1 ,  0
       0     0.1       0   97.47    0.06       0  219.37   0.045       0
   248.6    0.06       0  278.25    0.05       0  308.25    0.06       0
  318.25    0.05       0  408.25     0.1       0
Bank Sta=219.37,248.6
XS Rating Curve= 0 ,0
Exp/Cntr(USF)=0,0
Exp/Cntr=0.3,0.1

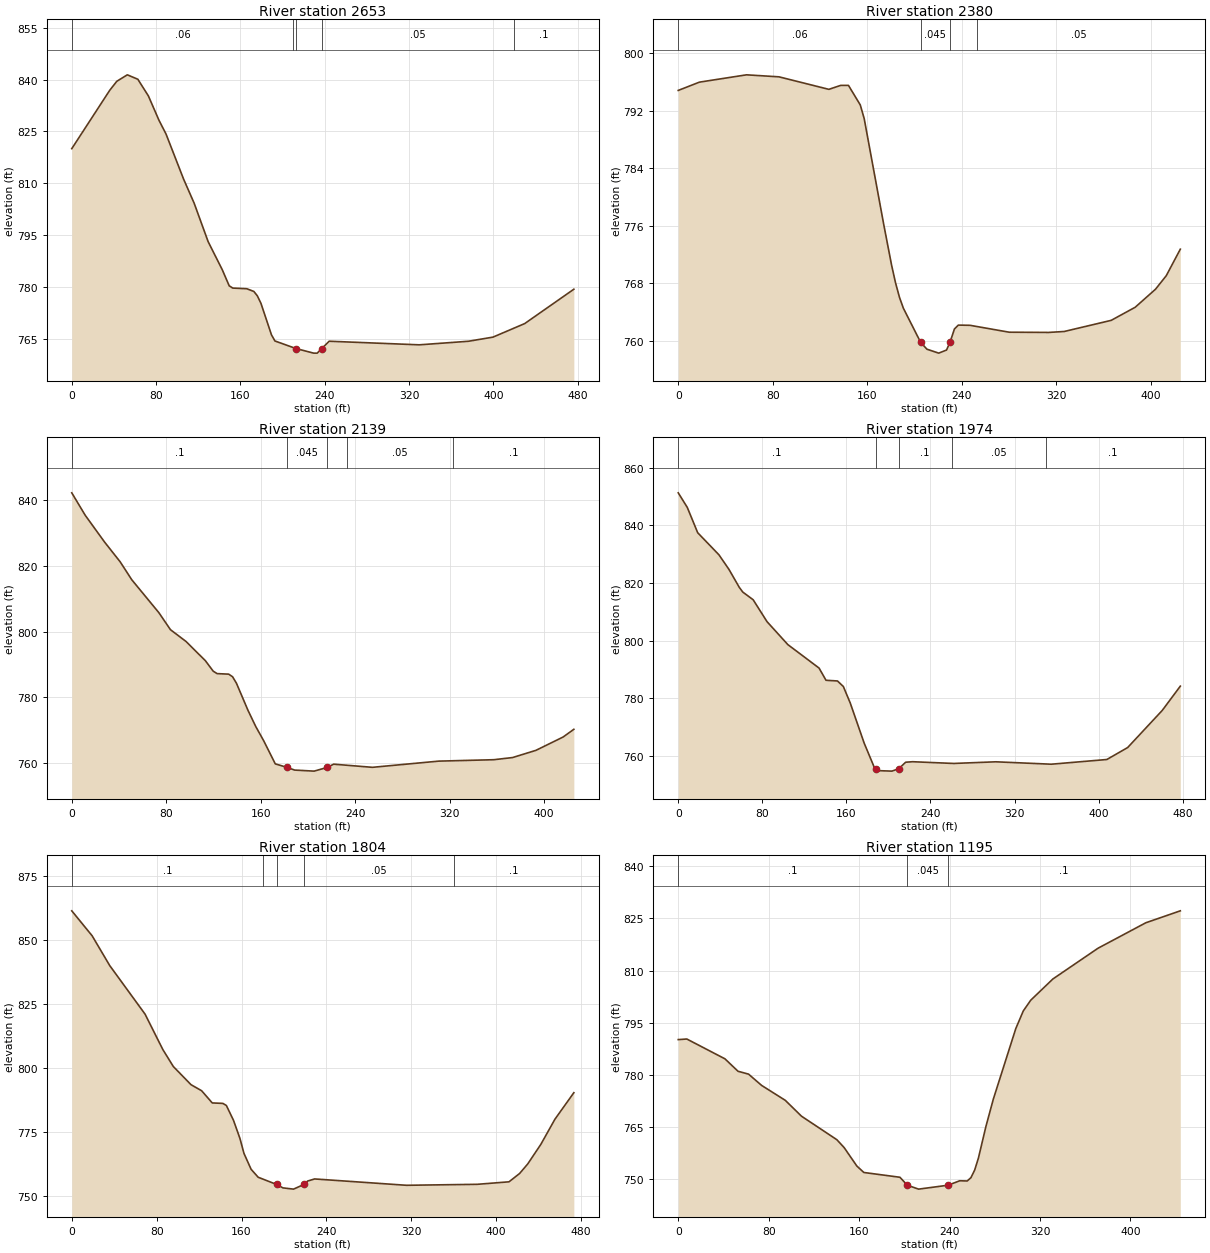
Type RM Length L Ch R = 1 ,2653    ,276.4,272.7,267.9
XS GIS Cut Line= 2
1642572.22751875462628.6573895961643040.58574473462716.003209579
#Sta/Elev= 30
       0  820.01    35.9  836.83    42.7  839.48    52.7  841.36    62.7  840.08
    72.7  835.26    82.7  828.25    89.4  824.27   106.1  811.21   116.1  804.26
   129.4  793.12   142.8     785   149.4  780.34   152.8  779.69   166.1   779.5
   172.8  778.71   176.1  777.44   179.5  775.29   189.5  766.16   192.8  764.39
  212.75762.2094   229.5  760.88   232.9  760.88  237.28762.2087   244.2  764.32
   329.7  763.28   376.4  764.31   399.7  765.51   429.8  769.43   476.4  779.36
#Mann= 5, -1 ,  0
       0    0.06       0     210    0.05       0  212.75   0.045       0
  237.28    0.05       0     420     0.1       0
Bank Sta=212.75,237.28
XS Rating Curve= 0 ,0
Exp/Cntr(USF)=0,0
Exp/Cntr=0.3,0.1

Type RM Length L Ch R = 1 ,2380    ,240.8,241.9,242.9
XS GIS Cut Line= 6
1642576.77672225462970.9270462541642663.22438401462957.396233425
1642737.32200484462945.7984875891642836.11905134 462930.33460775
1642910.21700026462918.7368619291642996.66433392462905.205721006
#Sta/Elev= 30
       0  794.86    17.9  796.01    57.8  797.03    85.3  796.75   127.5  795.01
   137.5  795.56   144.1  795.56   154.1  792.84   157.4  790.95     174  776.17
   180.6  770.55   183.9  768.12   187.3  766.06   190.6  764.55  205.12 759.835
   210.5  758.86   220.5  758.31   227.1  758.74  230.09759.8364   233.8  761.67
   237.1  762.21     247  762.18   280.2  761.22   313.5  761.19   326.7  761.32
   366.5  762.87   386.8  764.69     404   767.2   413.1  769.08     425  772.77
#Mann= 4, -1 ,  0
       0    0.06       0  205.12   0.045       0  230.09    0.06       0
   252.5    0.05       0
Bank Sta=205.12,230.09
XS Rating Curve= 0 ,0
Exp/Cntr(USF)=0,0
Exp/Cntr=0.3,0.1

Type RM Length L Ch R = 1 ,2139    ,164.5,164.9,165.2
XS GIS Cut Line= 6
1642632.25415261463185.4434463261642719.89702195463182.818451571
1642794.89162262463179.2137999861642894.44555737463169.783044579
1642969.11141853463162.7092398281643056.22148053463154.456959742
#Sta/Elev= 30
       0  842.34    11.4  835.49    27.8  827.32      41   821.3    50.8  815.84
    73.8  805.78    83.6   800.6    96.8     797   113.2  791.13   119.8  787.95
   123.1   787.2   132.9  787.04   136.2  786.25   139.5  784.27   149.3  775.98
   155.9  771.03   162.5  766.78   172.4  759.67  182.52758.5837   188.8  757.78
   205.3  757.46  216.47758.6002   221.8  759.58   254.7  758.62   310.8  760.51
   357.5  760.94   373.4   761.6   393.2   763.8   416.2  767.86   425.3  770.22
#Mann= 5, -1 ,  0
       0     0.1       0  182.52   0.045       0  216.47     0.1       0
  232.76    0.05       0  322.76     0.1       0
Bank Sta=182.52,216.47
XS Rating Curve= 0 ,0
Exp/Cntr(USF)=0,0
Exp/Cntr=0.3,0.1

Type RM Length L Ch R = 1 ,1974    ,170.4,170,169
XS GIS Cut Line= 2
1642638.38034008 463360.75803518 1643113.4415529463311.086755555
#Sta/Elev= 30
       0  851.26     8.6  846.22    18.5  837.44    38.7  829.79    48.2  824.76
    58.1  818.49    61.4  816.87    71.3  814.19    84.5   806.6   104.3  798.65
     134  790.52   140.6  786.29   151.5  786.05   157.1  784.13   163.7  778.37
   176.9  764.52   186.8  755.86  187.72755.6223   190.1  754.97   203.3   754.8
   209.8  755.63   216.4  757.89     223  758.06     262  757.46   302.2  758.03
     355   757.2   407.8  758.83   427.6  762.97   460.5  775.83   477.7  784.25
#Mann= 5, -1 ,  0
       0     0.1       0  187.72   0.045       0   209.8     0.1       0
     260    0.05       0     350     0.1       0
Bank Sta=187.72,209.8
XS Rating Curve= 0 ,0
Exp/Cntr(USF)=0,0
Exp/Cntr=0.3,0.1

Type RM Length L Ch R = 1 ,1804    ,593.2,609,603.9
XS GIS Cut Line= 2
1642664.18080508463541.1381274081643130.42061734 463460.13883799
#Sta/Elev= 30
       0  861.57    19.2  851.81    35.8  840.15    69.1  821.17    85.8  807.36
    95.7  800.71   112.4  793.59   122.4  791.23   132.4  786.46   142.4  786.28
   145.7  785.47   152.4  779.69   158.5  772.58   162.3  766.73     169  760.53
   175.7   757.4     193754.5944     199  753.25     209  752.76   218.9   754.6
   222.3  755.92   228.9  756.74   315.5  754.26   382.1  754.64   412.1  755.62
   422.1  758.88   429.8  762.64   442.1  770.27   455.4  780.11   473.2  790.46
#Mann= 5, -1 ,  0
       0     0.1       0     180    0.05       0     193   0.045       0
   218.9    0.05       0     360     0.1       0
Bank Sta=193,218.9
XS Rating Curve= 0 ,0
Exp/Cntr(USF)=0,0
Exp/Cntr=0.3,0.1

Type RM Length L Ch R = 1 ,1195    ,300.7,301.7,301
XS GIS Cut Line= 6
1643005.49305642463918.2821069211643082.56409651463848.536511511
1643154.31953043463818.7157050071643253.51519817 463806.05825001
1643327.91203101463796.5648306761643414.72911459463785.654747501
#Sta/Elev= 30
       0  790.19     7.6  790.36    41.3  784.67    52.9  781.09    62.2  780.27
    73.8  777.02    94.7  772.74     109  768.19   140.3  761.43   146.7  759.19
     158  753.86   164.2  752.01   196.1  750.64  202.61748.3579   212.6  747.23
  238.74748.3561     249  749.63   255.6  749.57   258.9  750.52   262.2  752.71
   265.5  756.12   272.1  765.16   278.7  773.08   298.6  793.38   305.2  798.42
   311.8  801.51   331.4  807.61   371.3  816.44   413.6  823.76   444.1  827.19
#Mann= 3, -1 ,  0
       0     0.1       0  202.61   0.045       0  238.74     0.1       0
Bank Sta=202.61,238.74
XS Rating Curve= 0 ,0
Exp/Cntr(USF)=0,0
Exp/Cntr=0.3,0.1

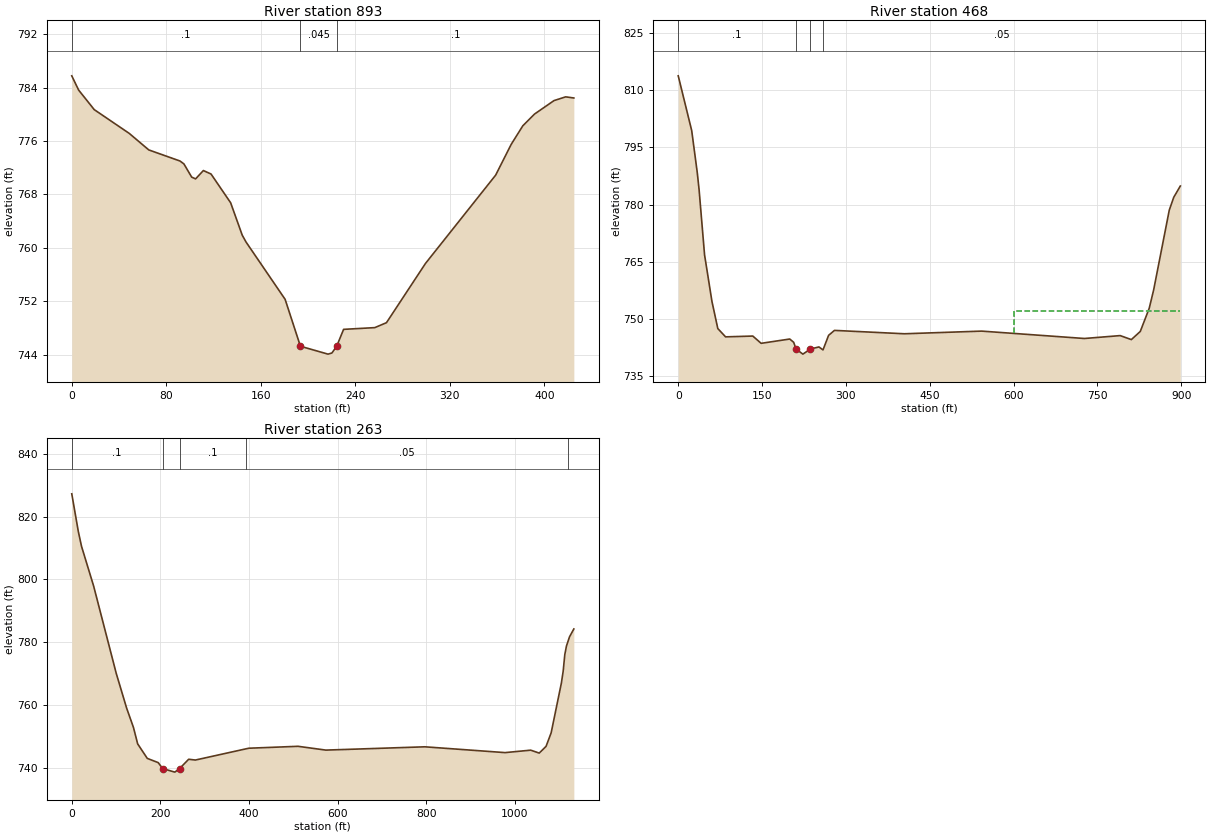
Type RM Length L Ch R = 1 ,893     ,416.5,424.5,426.5
XS GIS Cut Line= 6
 1643048.0051105464127.1891694221643135.03282359464118.108478919
1643209.62781876464110.3250299251643309.08792168464099.946769834
1643383.68291683464092.1633208391643470.71030185464083.082302257
#Sta/Elev= 30
       0  785.77     5.8  783.64      19  780.71    48.7  777.14    65.2  774.67
    91.6  773.01    94.9  772.58   101.5   770.6   104.8  770.33   111.4  771.58
   117.9  771.06   134.5  766.75   144.3   761.9   147.6  760.85   180.6  752.29
  193.55745.2604   216.9  744.08   220.2  744.25  224.25745.2586   230.1  747.79
   256.5  748.05   266.4  748.79   299.4  757.66   358.8  770.89     372  775.51
   381.8  778.28   391.7  780.04   408.2  782.06   418.1  782.62     425  782.45
#Mann= 3, -1 ,  0
       0     0.1       0  193.55   0.045       0  224.25     0.1       0
Bank Sta=193.55,224.25
XS Rating Curve= 0 ,0
Exp/Cntr(USF)=0,0
Exp/Cntr=0.3,0.1

Type RM Length L Ch R = 1 ,468     ,203.9,205.6,205.4
XS GIS Cut Line= 4
 1643164.1882771464438.3194526731643222.40026714464435.193797058
1643549.15703826464550.0247973581643830.75363746464144.741901903
#Sta/Elev= 30
       0  813.83    24.1  799.43      34  788.45    37.3  783.94    47.1  766.76
    60.4  754.46    70.8  747.39    84.7  745.21   133.4  745.42   148.3  743.51
   199.5  744.64   206.5  743.78  210.95741.9813     223  740.67236.4879742.0048
   251.7  742.56     259  741.78     269  745.61   279.5  746.91   404.6  746.02
   542.9  746.72   726.7  744.78   790.6  745.54   810.6  744.49   826.6  746.63
   842.6  752.73   850.5  757.54   878.5  778.55   886.5  781.91   898.2  784.86
#Mann= 4, -1 ,  0
       0     0.1       0  210.95   0.045       0236.4879     0.1       0
   258.3    0.05       0
#XS Ineff= 2 , 0
                          600.72          752.07
Permanent Ineff=
       F       F
Bank Sta=210.95,236.4879
XS Rating Curve= 0 ,0
Exp/Cntr(USF)=0,0
Exp/Cntr=0.3,0.1

Type RM Length L Ch R = 1 ,263     ,,,
XS GIS Cut Line= 4
1643073.17631023464571.3151161291643394.10840155464720.519814522
 1643543.5873428464673.658621405 1643869.9541876464143.508036403
#Sta/Elev= 30
       0   827.3    14.8  815.29      22  810.58    49.4  797.88   100.3   770.1
   123.7  759.04   139.3   752.8   148.7   747.6   170.4  742.97   195.1  741.62
  205.21739.7203   232.6  738.59  243.35739.7208   263.8  742.69   278.9  742.44
   399.5  746.21   510.6  746.82   573.4  745.61   796.8  746.66   977.9  744.81
  1035.7  745.59    1055  744.66  1070.4  746.81  1081.9  751.12    1105     767
  1109.1  770.85  1112.7  776.05  1116.3  778.72  1123.4  781.74  1133.1  784.22
#Mann= 5, -1 ,  0
       0     0.1       0  205.21   0.045       0  243.35     0.1       0
  393.92    0.05       0 1120.57     0.1       0
Bank Sta=205.21,243.35
XS Rating Curve= 0 ,0
Exp/Cntr(USF)=0,0
Exp/Cntr=0.3,0.1
LCMann Table=0

Chan Stop Cuts=-1
Use User Specified Reach Order=0
Composite Channel Slope=5